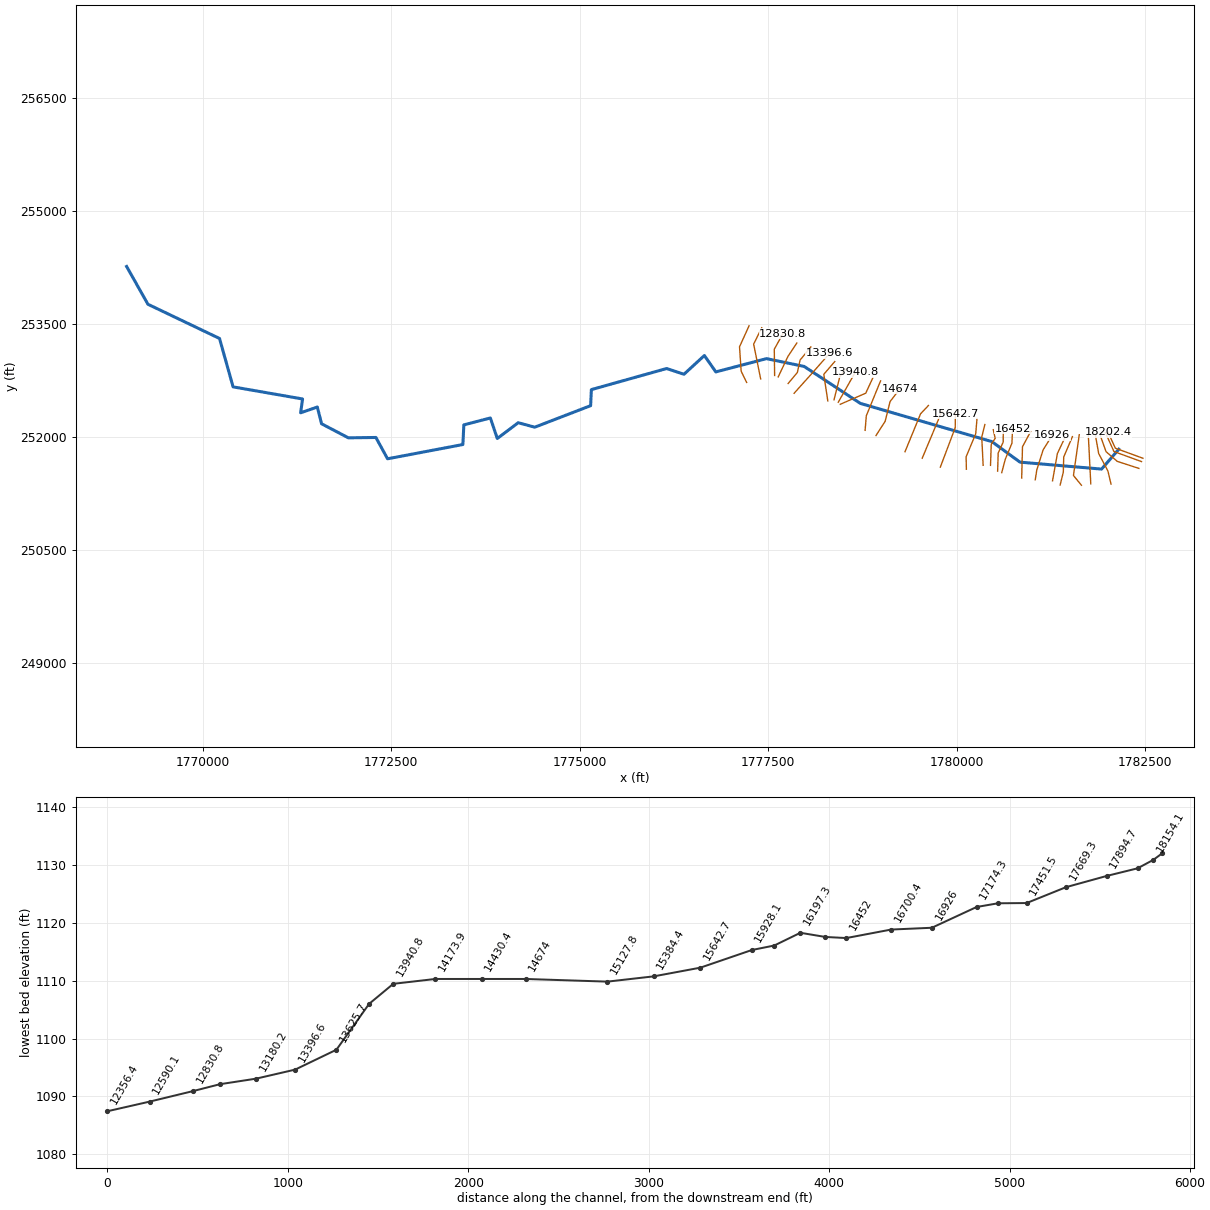
--- BUSHYFK1.prj (project) ---

Proj Title=BUSHYFK1
Current Plan=p01
Default Exp/Contr=0,0
English Units
Geom File=g01
Flow File=f01
Plan File=p01
BEGIN DESCRIPTION:
END DESCRIPTION:
DSS Export Rating Curves= 0
DSS Export Rating Curve Sorted= 0
DSS Export Volume Flow Curves= 0
DXF OffsetX= 0
DXF OffsetY= 0
DXF ScaleX= 0
DXF ScaleY= 0

--- BUSHYFK1.p01 (plan) ---

Plan Title=Floodplain
Program Version=4.00
Geom File=g01
Flow File=f01
K Sum by GR=0
Std Step Tol=0.01
Critical Tol=0.01
Num of Std Step Trials=20
Max Error Tol=0.3
Flow Tol Ratio=0.001
Split Flow NTrial=30
Split Flow Tol=0.02
Split Flow Ratio=0.02
Log Output Level=0
Friction Slope Method=1
Unsteady Friction Slope Method=2
Unsteady Bridges Friction Slope Method=1
Global Log Level=0
CheckData=False
Run HTab=0
Run UNet=0
Run PostProcess=0
UNET Theta=0
UNET Theta Warmup=0
UNET ZTol=0
UNET ZSATol=0
UNET MxIter=0
UNET MaxInSteps=0
UNET DtIC=0
UNET DtMin=0
UNET MaxCRTS=0
UNET WFStab=0
UNET SFStab=0
UNET WFX=0
UNET SFX=0
UNET DSS MLevel=0
UNET DZMax Abort=0
UNET Convert EG Bridges=0
UNET Use Existing IB Tables=0
UNET Froude Limit=0
UNET Froude Power=0
Write IC File=0
Echo Input=False
Echo Output=False
Write Detailed=0

--- BUSHYFK1.f01 (steady flow) ---

Flow Title=NFF Regression Equation
Program Version=5.03
Number of Profiles= 1
Profile Names=P100yr
River Rch & RM=BUSHYFK1,Main            ,18202.4
 1056.93
River Rch & RM=BUSHYFK1,Main            ,16926
1072.872
River Rch & RM=BUSHYFK1,Main            ,13180.2
1186.747
River Rch & RM=BUSHYFK1,Main            ,10736.3
1309.001
River Rch & RM=BUSHYFK1,Main            ,7813.9
1412.896
River Rch & RM=BUSHYFK1,Main            ,3118.3
1568.663
River Rch & RM=BUSHYFK1,Main            ,271.3
1721.494
Boundary for River Rch & Prof#=BUSHYFK1,Main            , 1
Up Type= 0
Dn Type= 3
Dn Slope=0.00321
DSS Import GetInterval= 0
DSS Import GetPeak= 0
DSS Import FillOption= 0

--- BUSHYFK1.g01 (geometry) ---

Geom Title=USGS 10m DEM
Program Version=4.10

River Reach=BUSHYFK1        ,Main
Reach XY= 30
     1782150.351       251838.83     1781922.178      251575.859
     1780839.958      251667.784     1780466.626      251940.422
     1778723.433      252446.303     1777976.941      252936.605
     1777477.661      253039.882     1776805.775       252864.17
     1776653.708      253081.214     1776382.814      252832.806
     1776153.154      252908.826     1775154.861      252629.432
     1775145.214      252416.686     1774403.891       252131.02
     1774184.885      252190.625      1773906.96      251981.381
     1773815.425      252253.288     1773463.365      252161.633
      1773450.59      251901.414     1772451.524      251712.345
     1772296.935      251994.984     1771932.116      251990.202
     1771576.351      252176.378     1771520.014      252398.542
     1771299.071      252322.271     1771324.255      252505.375
     1770402.787      252665.656     1770222.787      253307.331
     1769273.236      253760.712     1768990.461      254261.983

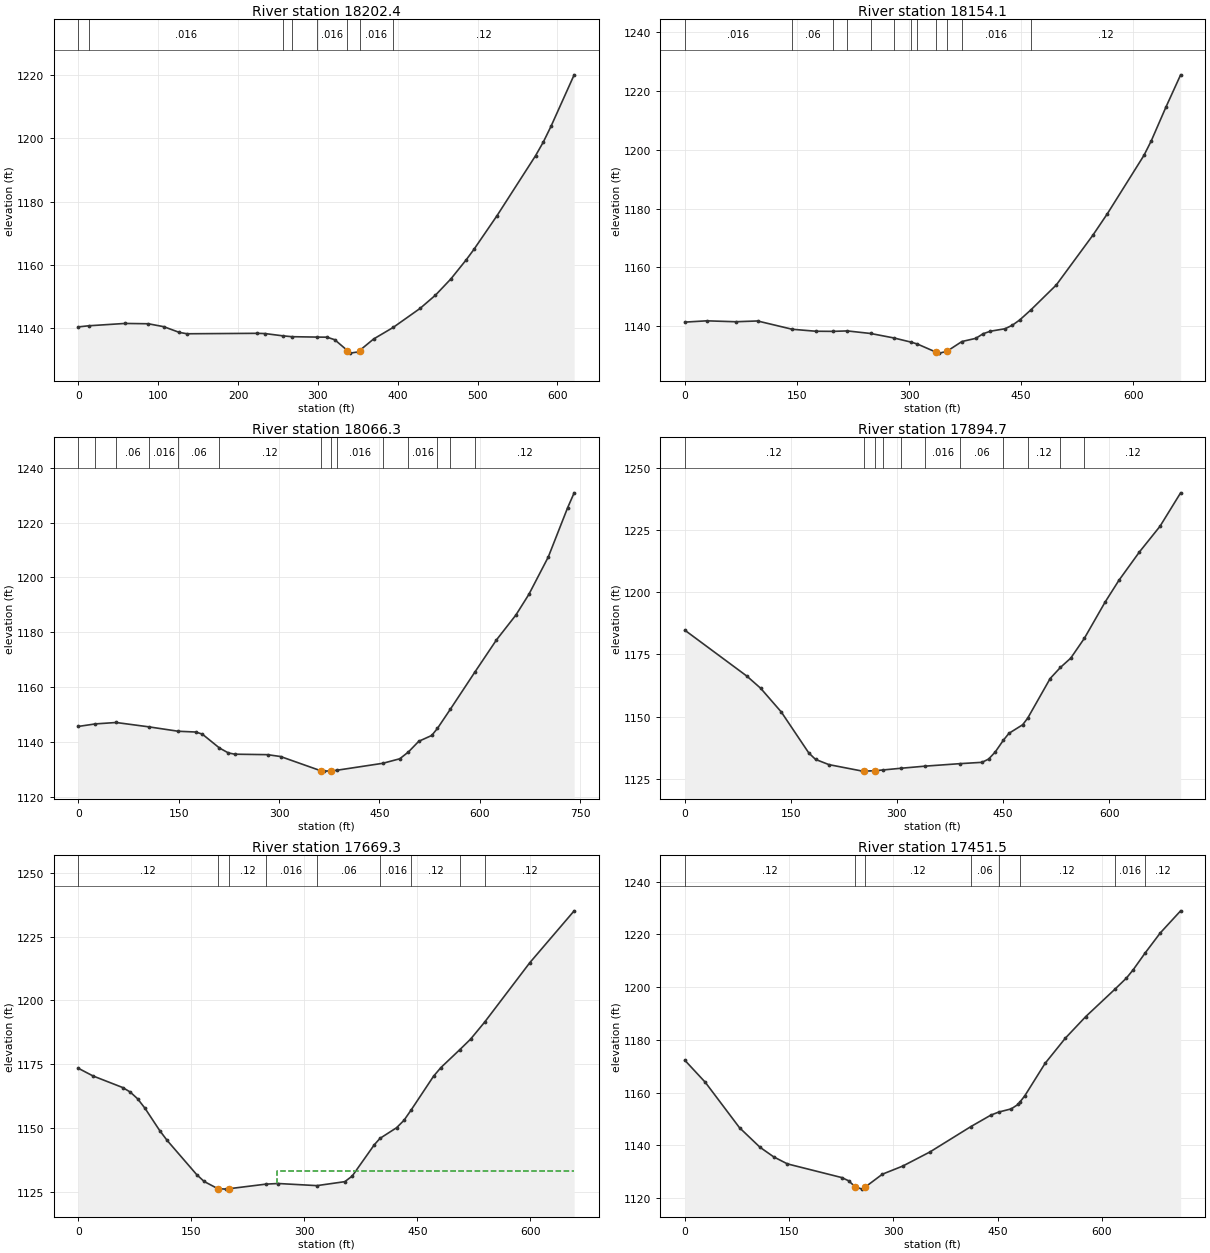
Type RM Length L Ch R = 1 ,18202.4 ,48.2,48.3,48.2
XS GIS Cut Line= 3
     1782470.374      251719.515     1782104.706      251852.978
     1782008.134      252063.482
#Sta/Elev= 30
       0  1140.3   13.071140.649    58.4 1141.39    87.6 1141.29     107 1140.36
   126.5 1138.55   136.2 1138.12   223.8 1138.26   233.6 1138.19  256.471137.454
  267.381137.195  298.63 1137.07   311.4 1137.04   321.1 1136.23  337.061132.782
   340.6 1131.99   350.3 1132.38  352.111132.786   369.8 1136.47  394.221140.118
   427.9 1146.14   447.2 1150.34   466.5 1155.48   485.8 1161.56   495.4 1164.84
   524.4 1175.55   572.6 1194.52   582.3 1198.84   591.9  1203.8   620.9 1220.11
#Mann= 8 ,-1 , 0
       0     .12       0   13.07    .016       0  256.47     .08       0
  267.38     .06       0  298.63    .016       0  337.06    .045       0
  352.11    .016       0  394.22     .12       0
Bank Sta=337.06,352.11
XS Rating Curve= 0 ,0
Exp/Cntr=0.3,0.1

Type RM Length L Ch R = 1 ,18154.1 ,96.1,87.8,79.6
XS GIS Cut Line= 3
     1782451.928      251675.027     1782086.259       251808.49
     1781973.412      252058.056
#Sta/Elev= 30
       0 1141.42    29.2 1141.86    68.1 1141.55    97.3 1141.81  143.561138.997
   175.2 1138.32  198.171138.276  217.38 1138.43  248.641137.556   279.91136.024
  303.081134.593  311.151133.969   335.5 1131.27   340.6 1130.88   350.5 1131.48
  370.641134.824   389.3 1135.91     399 1137.47   408.8 1138.33   428.4 1139.17
   438.2 1140.38     448 1142.16  462.821145.558   496.9 1154.05   545.8 1170.96
   565.3  1178.3   614.2 1198.12     624 1203.08   643.6 1214.54   663.2 1225.48
#Mann= 12 ,-1 , 0
       0    .016       0  143.56     .06       0  198.17    .016       0
  217.38     .08       0  248.64     .06       0   279.9     .12       0
  303.08    .016       0  311.15     .08       0   335.5    .045       0
   350.5     .12       0  370.64    .016       0  462.82     .12       0
Bank Sta=335.5,350.5
XS Rating Curve= 0 ,0
Exp/Cntr=0.3,0.1

Type RM Length L Ch R = 1 ,18066.3 ,180.6,171.5,163.3
XS GIS Cut Line= 4
     1782417.206      251584.966     1782129.662      251678.282
     1781981.008      251807.405     1781899.627       252035.27
#Sta/Elev= 30
       0  1145.7   25.641146.622   56.53 1147.13  105.471145.543  149.291143.942
   175.5 1143.66   185.3  1142.9  210.981137.832   224.3 1136.04     234 1135.58
   282.8 1135.41   302.3 1134.73  362.541129.537   367.9 1129.41   377.3 1129.51
  387.331129.761  455.211132.268   480.5 1133.91  493.421136.388   508.9 1140.28
   528.2  1142.4  536.811144.974  556.281152.028  592.451165.381     625 1177.21
   654.1 1186.29   673.4 1193.78   702.5 1207.43   731.5 1225.42   741.2 1230.82
#Mann= 14 ,-1 , 0
       0    .016       0   25.64     .08       0   56.53     .06       0
  105.47    .016       0  149.29     .06       0  210.98     .12       0
  362.54    .045       0   377.3     .12       0  387.33    .016       0
  455.21     .06       0  493.42    .016       0  536.81     .12       0
  556.28    .016       0  592.45     .12       0
Bank Sta=362.54,377.3
XS Rating Curve= 0 ,0
Exp/Cntr=0.3,0.1

Type RM Length L Ch R = 1 ,17894.7 ,232.4,225.4,215.5
XS GIS Cut Line= 5
     1782047.197      251377.718     1782006.607      251548.404
     1781967.629      251624.368     1781883.638      251781.517
     1781837.779       252039.61
#Sta/Elev= 30
       0 1184.78    87.7 1166.32   107.2 1161.44   136.5 1151.86   175.4 1135.38
   184.9 1132.81   203.9  1130.7   251.3 1128.09   253.3 1128.09   268.3 1128.23
  279.811128.547  306.271129.258  340.07  1130.1  388.931131.093   420.3 1131.63
   429.6 1132.93     439 1135.78  450.541140.527   458.4 1143.29   477.8 1146.74
  484.881149.377   516.7 1165.34  531.281169.807   545.8 1173.53  565.111181.528
   594.4 1196.07   613.8 1204.77   642.9 1216.22     672 1226.54   701.2 1240.01
#Mann= 11 ,-1 , 0
       0     .12       0   253.3    .045       0   268.3     .12       0
  279.81    .016       0  306.27     .12       0  340.07    .016       0
  388.93     .06       0  450.54    .016       0  484.88     .12       0
  531.28    .016       0  565.11     .12       0
Bank Sta=253.3,268.3
XS Rating Curve= 0 ,0
Exp/Cntr=0.3,0.1

Type RM Length L Ch R = 1 ,17669.3 ,222.5,217.9,212.1
XS GIS Cut Line= 2
     1781778.812      251380.271     1781745.548       252037.44
#Sta/Elev= 30
       0 1173.44    19.6 1170.42    58.9  1165.9    68.8 1164.16    78.6 1161.52
    88.4 1157.82     108 1149.06   117.8 1145.23   157.1 1131.82     167 1129.14
  185.051126.341   196.4 1126.15  200.111126.314  249.021128.108   265.2 1128.35
   316.61127.519   353.6 1129.07   363.4 1131.25   392.8 1143.52  400.37 1146.02
   422.3 1150.17   432.1 1153.05  441.641157.107   471.4 1170.33   481.2 1173.73
  506.321180.751   520.5 1184.83  539.161191.482   599.1 1214.74     658 1235.05
#Mann= 9 ,-1 , 0
       0     .12       0  185.05    .045       0  200.11     .12       0
  249.02    .016       0   316.6     .06       0  400.37    .016       0
  441.64     .12       0  506.32    .016       0  539.16     .12       0
#XS Ineff= 2 , 0
                          263.67         1133.18
Permanent Ineff=
       F       F
Bank Sta=185.05,200.11
XS Rating Curve= 0 ,0
Exp/Cntr=0.3,0.1

Type RM Length L Ch R = 1 ,17451.5 ,156.5,158.5,161
XS GIS Cut Line= 3
     1781655.487      251361.442      1781549.15      251490.565
      1781626.19      252030.929
#Sta/Elev= 30
       0  1172.3    29.5 1163.92    78.7  1146.7   108.2 1139.28   127.9 1135.64
   147.6 1132.98   225.8 1127.79   235.5 1126.59   245.2 1124.27     255 1123.41
  259.461124.194   284.2 1129.08   313.5 1132.16   352.5  1137.5  411.62 1147.16
   440.2 1151.48  451.651152.654   469.4 1153.84   479.2 1155.52  481.671156.348
   488.9 1158.77   518.2 1171.12   547.4 1180.69   576.6 1188.84  618.67 1199.25
   635.1 1203.44   644.9 1206.61  662.011212.955   683.9  1220.6   713.1 1228.96
#Mann= 8 ,-1 , 0
       0     .12       0   245.2    .045       0  259.46     .12       0
  411.62     .06       0  451.65    .016       0  481.67     .12       0
  618.67    .016       0  662.01     .12       0
Bank Sta=245.2,259.46
XS Rating Curve= 0 ,0
Exp/Cntr=0.3,0.1

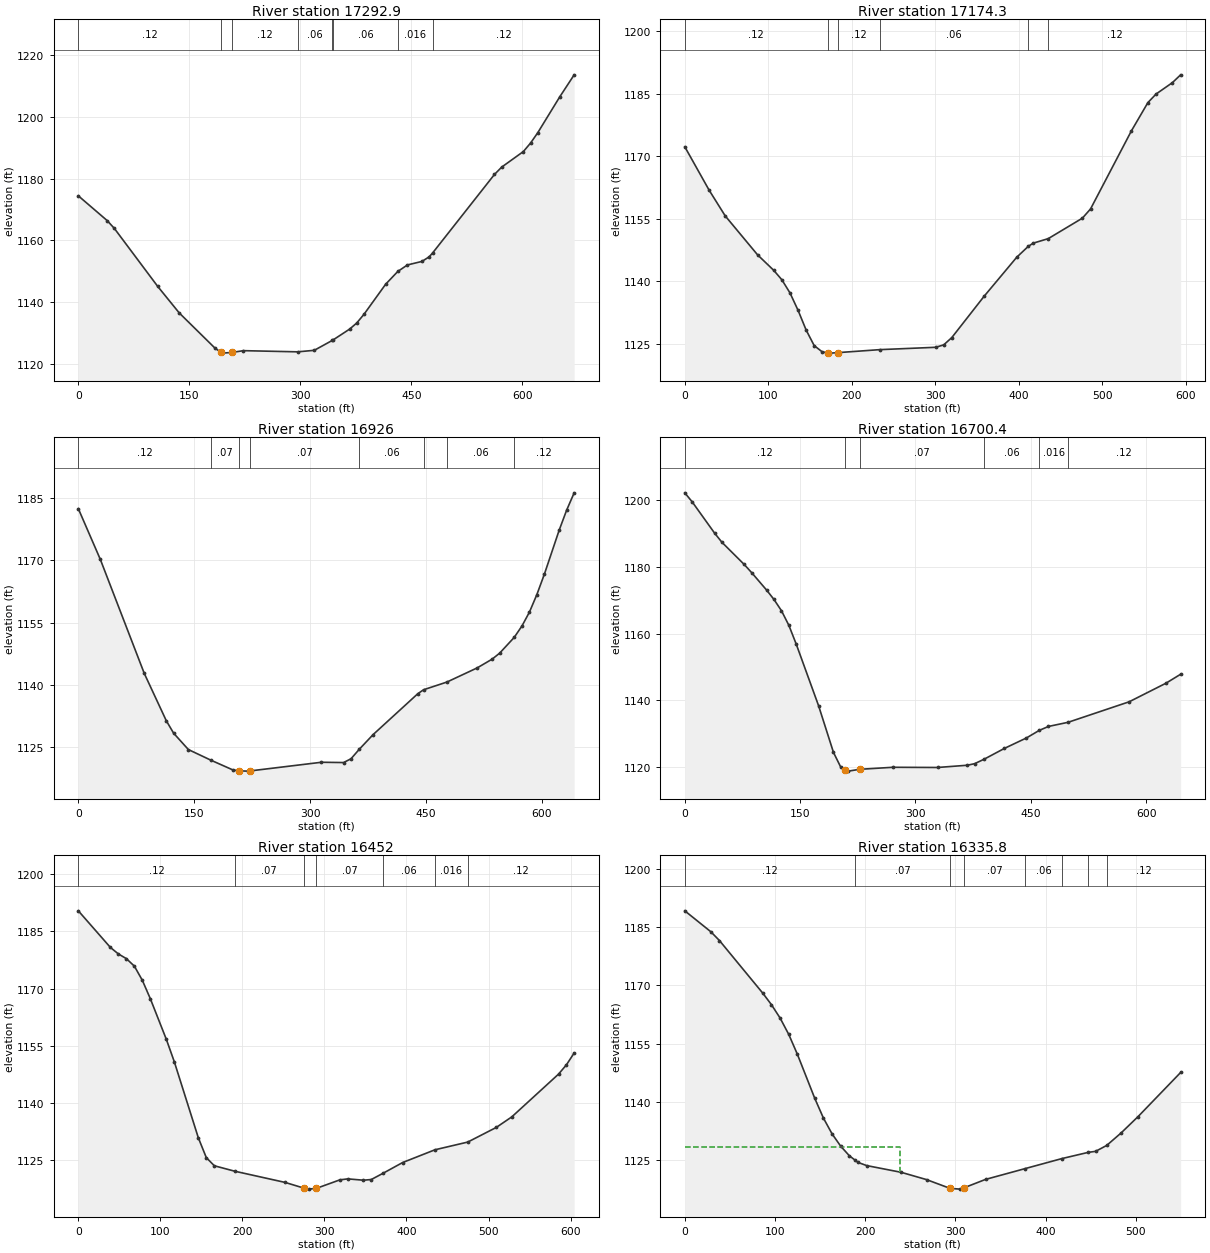
Type RM Length L Ch R = 1 ,17292.9 ,121.7,118.6,114.7
XS GIS Cut Line= 4
     1781372.342      251364.991     1781414.601      251535.053
     1781419.844      251735.824     1781535.044      252005.973
#Sta/Elev= 30
       0 1174.43    38.9 1166.41    48.7 1163.84   107.1 1145.07   136.3 1136.42
   184.8 1124.95  192.051123.756   194.4 1123.37  207.93  1123.6     223 1124.17
  296.35 1123.79   318.7 1124.28  343.16 1127.51  344.471127.707   366.5 1131.17
   376.1 1133.15   385.9 1135.98   415.2 1145.75  431.541149.881   444.6    1152
   464.2 1153.14     474 1154.64  478.691155.913   562.1 1181.36   571.9 1183.75
   601.2 1188.81     611 1191.59   620.8 1194.98   650.2 1206.51   669.8 1213.71
#Mann= 8 ,-1 , 0
       0     .12       0  192.05    .045       0  207.93     .12       0
  296.35     .06       0  343.16     .12       0  344.47     .06       0
  431.54    .016       0  478.69     .12       0
Bank Sta=192.05,207.93
XS Rating Curve= 0 ,0
Exp/Cntr=0.3,0.1

Type RM Length L Ch R = 1 ,17174.3 ,251,248.3,245.2
XS GIS Cut Line= 3
     1781271.372      251420.643     1781336.476      251783.056
     1781433.048      251987.049
#Sta/Elev= 30
       0 1172.29    29.1 1161.88    48.4 1155.69    87.2 1146.33   106.6  1142.6
   116.3 1140.34     126 1137.19   135.7    1133   145.4 1128.25     155 1124.53
   164.7 1123.02  171.021122.831   174.4 1122.73   184.1 1122.86  233.481123.566
   300.4 1124.13   310.1 1124.71   319.8 1126.46   358.5 1136.38   397.6 1145.76
  411.271148.346   417.3 1149.14   435.31150.224   476.2 1155.14     486 1157.36
     535 1176.13   554.7  1182.9   564.5 1184.96   584.1  1187.7   593.9 1189.57
#Mann= 6 ,-1 , 0
       0     .12       0  171.02    .045       0   184.1     .12       0
  233.48     .06       0  411.27    .016       0   435.3     .12       0
Bank Sta=171.02,184.1
XS Rating Curve= 0 ,0
Exp/Cntr=0.3,0.1

Type RM Length L Ch R = 1 ,16926   ,219.2,225.6,232
XS GIS Cut Line= 4
     1781042.423      251434.141     1781063.039      251565.435
     1781146.589      251830.192     1781269.202      252026.589
#Sta/Elev= 30
       0  1182.5    28.5 1170.25    85.4 1142.73   113.9 1131.31   123.4  1128.3
   142.5 1124.35   171.81121.771   199.9 1119.45   207.9 1119.21   219.1 1119.14
   222.9  1119.2   314.8 1121.28   343.5 1121.21   353.1 1122.12  363.971124.447
   381.8 1127.97   439.5 1137.81  447.041138.784  477.291140.643   516.6 1144.07
   535.9 1146.18   545.6 1147.62   564.41151.411   574.5 1154.18   584.2 1157.54
   593.8 1161.76   603.5 1166.67   622.8 1177.37   632.4 1182.16   642.1 1186.33
#Mann= 8 ,-1 , 0
       0     .12       0   171.8     .07       0   207.9    .045       0
   222.9     .07       0  363.97     .06       0  447.04    .016       0
  477.29     .06       0   564.4     .12       0
Bank Sta=207.9,222.9
XS Rating Curve= 0 ,0
Exp/Cntr=0.3,0.1

Type RM Length L Ch R = 1 ,16700.4 ,256.7,248.4,239.6
XS GIS Cut Line= 3
     1780862.301      251456.928     1780873.152      251872.509
     1780981.659      252074.332
#Sta/Elev= 30
       0  1202.1     9.7 1199.37    38.7 1190.06    48.3  1187.3    77.3 1180.66
      87 1178.21   106.4    1173     116 1170.19   125.7 1166.84   135.4 1162.43
     145 1156.79     174  1138.4   193.4 1124.42     203 1119.95  208.661119.298
   212.7 1118.83  227.321119.372   270.7 1119.98   328.7 1119.92   367.4 1120.59
     377 1121.06  389.411122.408   415.7 1125.63   444.4 1128.76  460.861131.001
     473  1132.2  498.521133.439     578 1139.58   625.8 1145.13   644.9 1147.82
#Mann= 6 ,-1 , 0
       0     .12       0  208.66    .045       0  227.32     .07       0
  389.41     .06       0  460.86    .016       0  498.52     .12       0
Bank Sta=208.66,227.32
XS Rating Curve= 0 ,0
Exp/Cntr=0.3,0.1

Type RM Length L Ch R = 1 ,16452   ,117.1,116.2,115.4
XS GIS Cut Line= 4
     1780597.544      251528.542     1780645.287      251707.579
     1780733.178      251919.167     1780740.773      252109.054
#Sta/Elev= 30
       0 1190.42      39 1180.83    48.8  1179.1    58.5 1177.88    68.3  1175.9
      78 1172.19    87.8 1167.33   107.3 1156.67     117 1150.79   146.3 1130.82
     156 1125.63   165.8 1123.49  190.541122.071   252.1 1119.12  274.491117.654
   280.8 1117.36   290.3 1117.57   318.9  1119.8   328.5 1120.05   347.6  1119.7
   357.1 1119.88  371.68 1121.55   395.3 1124.34  434.711127.688  474.711129.714
   509.4 1133.55   528.4 1136.33   585.4 1147.56     595    1150   604.4  1153.1
#Mann= 7 ,-1 , 0
       0     .12       0  190.54     .07       0  274.49    .045       0
   290.3     .07       0  371.68     .06       0  434.71    .016       0
  474.71     .12       0
Bank Sta=274.49,290.3
XS Rating Curve= 0 ,0
Exp/Cntr=0.3,0.1

Type RM Length L Ch R = 1 ,16335.8 ,142.1,138.4,134.3
XS GIS Cut Line= 4
     1780543.291      251549.159     1780550.886      251788.959
     1780617.075      251933.273      1780618.16      252084.098
#Sta/Elev= 30
       0 1189.13    28.8 1183.76    38.4 1181.49    86.4 1167.96      96    1165
   105.6 1161.56   115.2 1157.35   124.8 1152.22     144 1140.92   153.6 1135.84
   163.2 1131.77   172.7 1128.62   182.3 1126.15  188.451125.048   191.9 1124.43
   201.5 1123.61   239.9 1121.87   267.9    1120   294.1 1117.73   305.3 1117.55
   309.1 1117.86   333.3 1120.05  377.17 1122.83  417.811125.401  447.351127.018
   455.2 1127.26  467.531128.781   483.5 1131.99   502.4 1136.22   549.5 1147.55
#Mann= 8 ,-1 , 0
       0     .12       0  188.45     .07       0   294.1    .045       0
   309.1     .07       0  377.17     .06       0  417.81     .08       0
  447.35    .016       0  467.53     .12       0
#XS Ineff= 2 , 0
          238.39 1128.38
Permanent Ineff=
       F       F
Bank Sta=294.1,309.1
XS Rating Curve= 0 ,0
Exp/Cntr=0.3,0.1

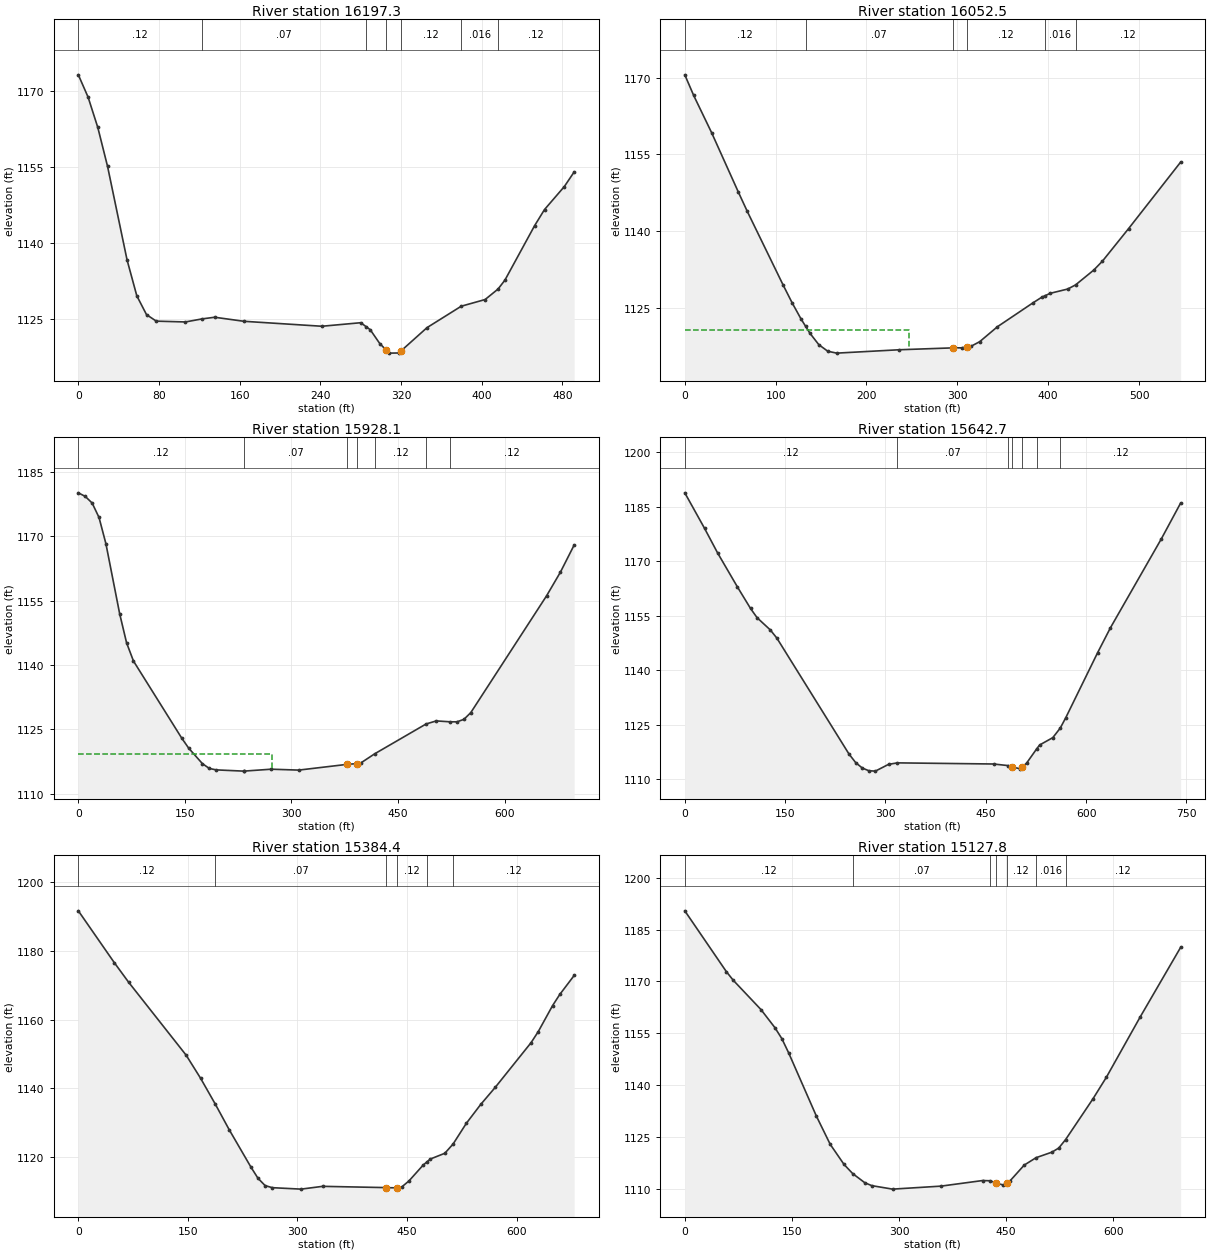
Type RM Length L Ch R = 1 ,16197.3 ,130.2,144.8,159.3
XS GIS Cut Line= 4
      1780448.89      251625.114     1780458.655      251905.061
     1780510.739      251983.186     1780485.782      252098.204
#Sta/Elev= 30
       0 1173.26     9.7 1168.84    19.3 1162.86      29 1155.15    48.3  1136.7
      58 1129.59    67.6 1125.88    77.3 1124.59   106.2 1124.43  122.63 1125.03
   135.2 1125.36   164.2 1124.56   241.5 1123.58   280.1 1124.28  285.571123.471
   289.5 1122.89   298.9 1120.17   305.3 1118.88   308.3 1118.27   317.7  1118.3
   320.3 1118.76   345.8 1123.31  379.721127.539   403.4 1128.86  416.161130.921
     423 1132.68   452.5 1143.46   462.3 1146.64   481.9 1151.17   491.7 1154.07
#Mann= 7 ,-1 , 0
       0     .12       0  122.63     .07       0  285.57     .12       0
   305.3    .045       0   320.3     .12       0  379.72    .016       0
  416.16     .12       0
Bank Sta=305.3,320.3
XS Rating Curve= 0 ,0
Exp/Cntr=0.3,0.1

Type RM Length L Ch R = 1 ,16052.5 ,134.5,124.5,114.4
XS GIS Cut Line= 3
     1780351.233      251626.199     1780332.787      251999.462
      1780374.02      252166.563
#Sta/Elev= 30
       0 1170.61     9.8 1166.56    29.5 1159.28      59 1147.61    68.8 1143.84
   108.2 1129.43     118 1125.98   127.8 1122.81  133.111121.292   137.7 1119.98
   147.5 1117.73   157.4 1116.44   167.2 1116.07     236 1116.73     295  1117.1
   304.9 1117.11  310.841117.276   314.7 1117.38   324.6 1118.31   344.2 1121.25
   383.3 1125.93   392.8 1127.01  396.621127.324   402.4  1127.8   421.5 1128.63
  430.171129.443   450.2 1132.35   459.8 1134.11   488.5 1140.47   545.8  1153.5
#Mann= 6 ,-1 , 0
       0     .12       0  133.11     .07       0     295    .045       0
  310.84     .12       0  396.62    .016       0  430.17     .12       0
#XS Ineff= 2 , 0
          247.06 1120.52
Permanent Ineff=
       F       F
Bank Sta=295,310.84
XS Rating Curve= 0 ,0
Exp/Cntr=0.3,0.1

Type RM Length L Ch R = 1 ,15928.1 ,284.5,285.4,286.2
XS GIS Cut Line= 4
     1780128.794      251574.115     1780125.539      251739.046
     1780252.492      252042.865     1780269.853      252245.773
#Sta/Elev= 30
       0 1180.13     9.7  1179.3    19.4 1177.76    29.1  1174.4    38.8 1168.29
    58.2 1151.94    67.9 1145.19    77.6 1140.94   145.6 1122.96   155.3 1120.65
   174.6 1117.04   184.3 1115.92     194 1115.58   232.8 1115.29  233.041115.292
   271.5 1115.74   310.2 1115.53     378 1116.86   392.11117.039   397.4 1117.17
  417.131119.325  489.541126.282   503.9 1126.99  523.31 1126.78     533 1126.78
   542.7 1127.35   552.4 1128.92   659.1 1156.14   678.5 1161.63   697.9 1167.97
#Mann= 7 ,-1 , 0
       0     .12       0  233.04     .07       0     378    .045       0
   392.1     .07       0  417.13     .12       0  489.54    .016       0
  523.31     .12       0
#XS Ineff= 2 , 0
          272.34 1119.32
Permanent Ineff=
       F       F
Bank Sta=378,392.1
XS Rating Curve= 0 ,0
Exp/Cntr=0.3,0.1

Type RM Length L Ch R = 1 ,15642.7 ,258.9,258.2,257
XS GIS Cut Line= 3
     1779783.742      251602.327     1779981.225      252126.416
      1779982.31      252307.622
#Sta/Elev= 30
       0 1188.78    29.5 1179.02    49.1 1172.23    78.6 1162.92    98.3 1156.97
   108.1 1154.43   127.7  1151.1   137.6 1148.84   245.6 1116.91   255.5 1114.58
   265.3  1113.1   275.1 1112.35   284.9 1112.24   304.6  1114.1  317.861114.511
   461.8  1114.2  483.43 1113.76  488.68 1113.38   501.1 1112.92  503.761113.325
   510.9 1114.41  526.131118.377   530.6 1119.44   550.2 1121.45  561.37 1124.09
   569.6 1126.94   617.3 1144.85   636.4 1151.68   712.7  1176.2   741.3 1185.96
#Mann= 7 ,-1 , 0
       0     .12       0  317.86     .07       0  483.43     .12       0
  488.68    .045       0  503.76     .12       0  526.13    .016       0
  561.37     .12       0
Bank Sta=488.68,503.76
XS Rating Curve= 0 ,0
Exp/Cntr=0.3,0.1

Type RM Length L Ch R = 1 ,15384.4 ,256.6,256.7,256.5
XS GIS Cut Line= 2
     1779542.857      251719.515     1779805.443        252345.6
#Sta/Elev= 30
       0 1191.63    49.2 1176.58    68.9 1170.87   147.6 1149.68   167.3    1143
  187.531135.452   206.6    1128   236.2 1117.19     246 1113.89   255.8 1111.76
   265.7 1111.16     305 1110.74   334.5 1111.55   421.8 1111.18   436.8  1111.1
   442.8 1111.37   452.6  1113.1   472.3 1117.76  477.011118.596   482.1  1119.5
   501.8 1121.16  513.141123.854   531.3 1129.88     551 1135.37   570.7 1140.28
   619.9 1153.31   629.7 1156.51   649.4  1164.1   659.2 1167.32   678.9 1172.84
#Mann= 6 ,-1 , 0
       0     .12       0  187.53     .07       0   421.8    .045       0
   436.8     .12       0  477.01    .016       0  513.14     .12       0
Bank Sta=421.8,436.8
XS Rating Curve= 0 ,0
Exp/Cntr=0.3,0.1

Type RM Length L Ch R = 1 ,15127.8 ,449.6,453.8,457.2
XS GIS Cut Line= 3
     1779314.992       251806.32     1779521.155      252308.707
     1779625.322      252418.299
#Sta/Elev= 30
       0 1190.46    58.2 1172.84    67.9 1170.33   106.7 1161.84   126.1 1156.63
   135.8 1153.46   145.5 1149.27   184.2    1131   203.6 1122.81     223 1116.97
   235.11114.325   252.1 1111.67   261.8 1110.84   290.9 1109.83   358.8  1110.7
     417 1112.32  427.471112.252   436.4 1111.58   446.1 1111.01  450.631111.623
   455.8 1112.32   475.2 1116.79  491.831118.939     514 1120.54   523.6 1121.74
  533.211124.201   571.4 1135.97   590.3 1142.26   637.5 1159.68   694.2 1179.87
#Mann= 7 ,-1 , 0
       0     .12       0   235.1     .07       0  427.47     .12       0
   436.4    .045       0  450.63     .12       0  491.83    .016       0
  533.21     .12       0
Bank Sta=436.4,450.63
XS Rating Curve= 0 ,0
Exp/Cntr=0.3,0.1

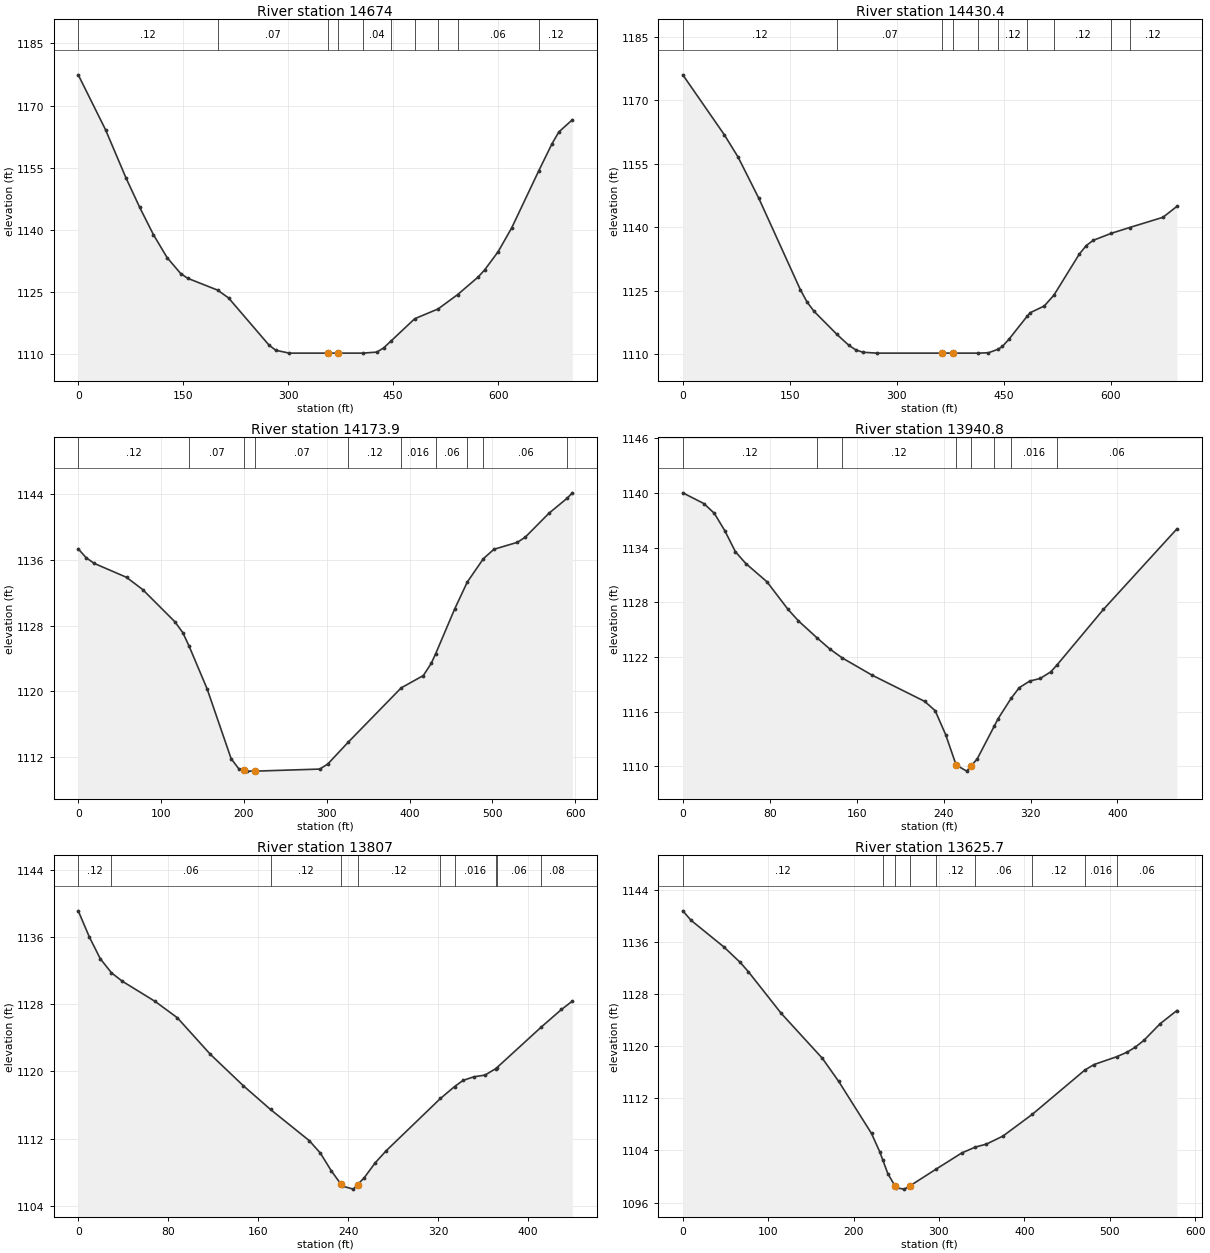
Type RM Length L Ch R = 1 ,14674   ,246.1,243.5,239.9
XS GIS Cut Line= 4
     1778929.792      252020.079      1779051.32      252208.881
     1779116.424      252470.383     1779245.548      252638.568
#Sta/Elev= 30
       0  1177.4      39 1164.16    68.3 1152.51    87.9 1145.41   107.4 1138.87
   126.9 1133.34   146.4 1129.48   156.2 1128.35  199.071125.489   214.8  1123.6
   272.7  1112.2   282.3 1110.98   301.5 1110.29   356.6 1110.29   371.6 1110.29
  406.61 1110.29   426.6 1110.54   436.3 1111.54  447.411113.292  480.71 1118.58
  514.111120.941  542.161124.415   571.1  1128.6   580.8 1130.38     600 1134.76
   619.3 1140.48  657.661154.134   677.1 1160.84   686.8 1163.64     706 1166.56
#Mann= 10 ,-1 , 0
       0     .12       0  199.07     .07       0   356.6    .045       0
   371.6     .07       0  406.61     .04       0  447.41     .12       0
  480.71    .016       0  514.11     .12       0  542.16     .06       0
  657.66     .12       0
Bank Sta=356.6,371.6
XS Rating Curve= 0 ,0
Exp/Cntr=0.3,0.1

Type RM Length L Ch R = 1 ,14430.4 ,273.8,256.5,238.7
XS GIS Cut Line= 3
     1778785.478      252089.523     1778801.754      252282.666
     1778990.556      252744.905
#Sta/Elev= 30
       0 1176.01    58.2 1161.86    77.5  1156.6   106.6 1146.86   164.8 1125.31
   174.4 1122.33   184.1 1120.16  216.271114.706     233 1112.12   242.8 1111.05
   252.6  1110.5   272.2 1110.29   363.4 1110.29   378.4 1110.29  414.46 1110.29
   428.8 1110.38  442.331111.205   448.4 1111.88   458.2 1113.72  483.071119.014
   487.5 1119.85   507.1 1121.43  520.651124.002   556.1 1133.66   565.9 1135.68
   575.6 1136.92  601.231138.593  626.681139.946   673.6 1142.37   693.1 1144.95
#Mann= 10 ,-1 , 0
       0     .12       0  216.27     .07       0   363.4    .045       0
   378.4     .07       0  414.46     .04       0  442.33     .12       0
  483.07    .016       0  520.65     .12       0  601.23     .08       0
  626.68     .12       0
Bank Sta=363.4,378.4
XS Rating Curve= 0 ,0
Exp/Cntr=0.3,0.1

Type RM Length L Ch R = 1 ,14173.9 ,217.7,233.1,247.2
XS GIS Cut Line= 3
     1778455.617      252434.575     1778794.159      252582.145
     1778889.645      252788.308
#Sta/Elev= 30
       0 1137.33     9.7 1136.24    19.4 1135.56    58.3 1133.87    77.8 1132.38
   116.6 1128.47   126.3 1127.13  133.881125.483   155.5 1120.32   184.6  1111.8
   194.4  1110.5   199.6 1110.39   204.1 1110.29   213.8 1110.29   291.6 1110.54
   301.3 1111.16  325.711113.788  389.861120.418   416.6 1121.92   426.1 1123.39
  431.521124.582   454.5 1130.03  469.721133.302  489.071136.134   501.8 1137.28
   530.2 1138.13   539.7 1138.76   568.1 1141.65  590.451143.513   596.5 1144.15
#Mann= 10 ,-1 , 0
       0     .12       0  133.88     .07       0   199.6    .045       0
   213.8     .07       0  325.71     .12       0  389.86    .016       0
  431.52     .06       0  469.72     .12       0  489.07     .06       0
  590.45     .12       0
Bank Sta=199.6,213.8
XS Rating Curve= 0 ,0
Exp/Cntr=0.3,0.1

Type RM Length L Ch R = 1 ,13940.8 ,127.6,133.8,140
XS GIS Cut Line= 2
     1778429.659         252462.     1778654.101      252857.455
#Sta/Elev= 30
       0 1140.03    19.4 1138.85      29 1137.78    38.7 1135.86    48.4 1133.56
      58 1132.26    77.4 1130.26    96.8 1127.23   106.4 1125.96  123.631124.083
   135.4 1122.86  146.651121.895   174.1    1120   222.5 1117.12   232.2  1116.1
   241.9 1113.46   251.5 1110.13   261.2 1109.45  265.611110.062   270.9 1110.79
   286.61114.391   290.2 1115.22  302.151117.453   309.6 1118.62   319.3 1119.35
   328.9 1119.63   338.6 1120.36  344.141121.085     387 1127.21   454.7 1136.07
#Mann= 8 ,-1 , 0
       0     .12       0  123.63     .06       0  146.65     .12       0
   251.5    .045       0  265.61     .12       0   286.6     .08       0
  302.15    .016       0  344.14     .06       0
Bank Sta=251.5,265.61
XS Rating Curve= 0 ,0
Exp/Cntr=0.3,0.1

Type RM Length L Ch R = 1 ,13807   ,172.4,181.3,190.2
XS GIS Cut Line= 3
     1778373.152      252494.254     1778449.107      252798.074
     1778525.062      252898.985
#Sta/Elev= 30
       0 1139.11     9.8 1136.02    19.6 1133.41   29.561131.733    39.2 1130.73
    68.5 1128.32    88.1 1126.39   117.4 1122.05   146.8  1118.3  171.051115.468
   205.5 1111.76   215.3 1110.29   225.1 1108.17   233.61106.593   234.9 1106.35
   244.7 1105.99  248.47 1106.52   254.4 1107.35   264.2 1109.13     274 1110.57
  322.181116.781  334.77  1118.2   342.3 1118.93     352 1119.36   361.8 1119.56
  371.291120.323  372.41 1120.45     4121125.295   429.8 1127.37   439.5 1128.36
#Mann= 10 ,-1 , 0
       0     .12       0   29.56     .06       0  171.05     .12       0
   233.6    .045       0  248.47     .12       0  322.18     .06       0
  334.77    .016       0  371.29     .12       0  372.41     .06       0
     412     .08       0
Bank Sta=233.6,248.47
XS Rating Curve= 0 ,0
Exp/Cntr=0.3,0.1

Type RM Length L Ch R = 1 ,13625.7 ,249,229.2,208.7
XS GIS Cut Line= 3
     1778290.687      252480.148     1778237.518      252831.711
     1778382.917      253000.982
#Sta/Elev= 30
       0 1140.85     9.6  1139.4      48 1135.31    67.3 1132.91    76.9 1131.47
   115.3 1125.08   163.4 1118.18   182.6 1114.62     221 1106.62   230.6 1103.82
  234.111102.577   240.2 1100.42  248.571098.538   249.8 1098.26   259.5 1098.06
  265.761098.537  296.011101.081   326.7 1103.62  342.741104.532   355.6 1104.98
     375 1106.22  409.251109.553   470.81116.361   481.7 1117.22  508.431118.431
   520.5 1119.13   530.2 1119.91   539.9 1120.92   559.3 1123.52   578.7 1125.52
#Mann= 9 ,-1 , 0
       0     .12       0  234.11     .07       0  248.57    .045       0
  265.76     .07       0  296.01     .12       0  342.74     .06       0
  409.25     .12       0   470.8    .016       0  508.43     .06       0
Bank Sta=248.57,265.76
XS Rating Curve= 0 ,0
Exp/Cntr=0.3,0.1

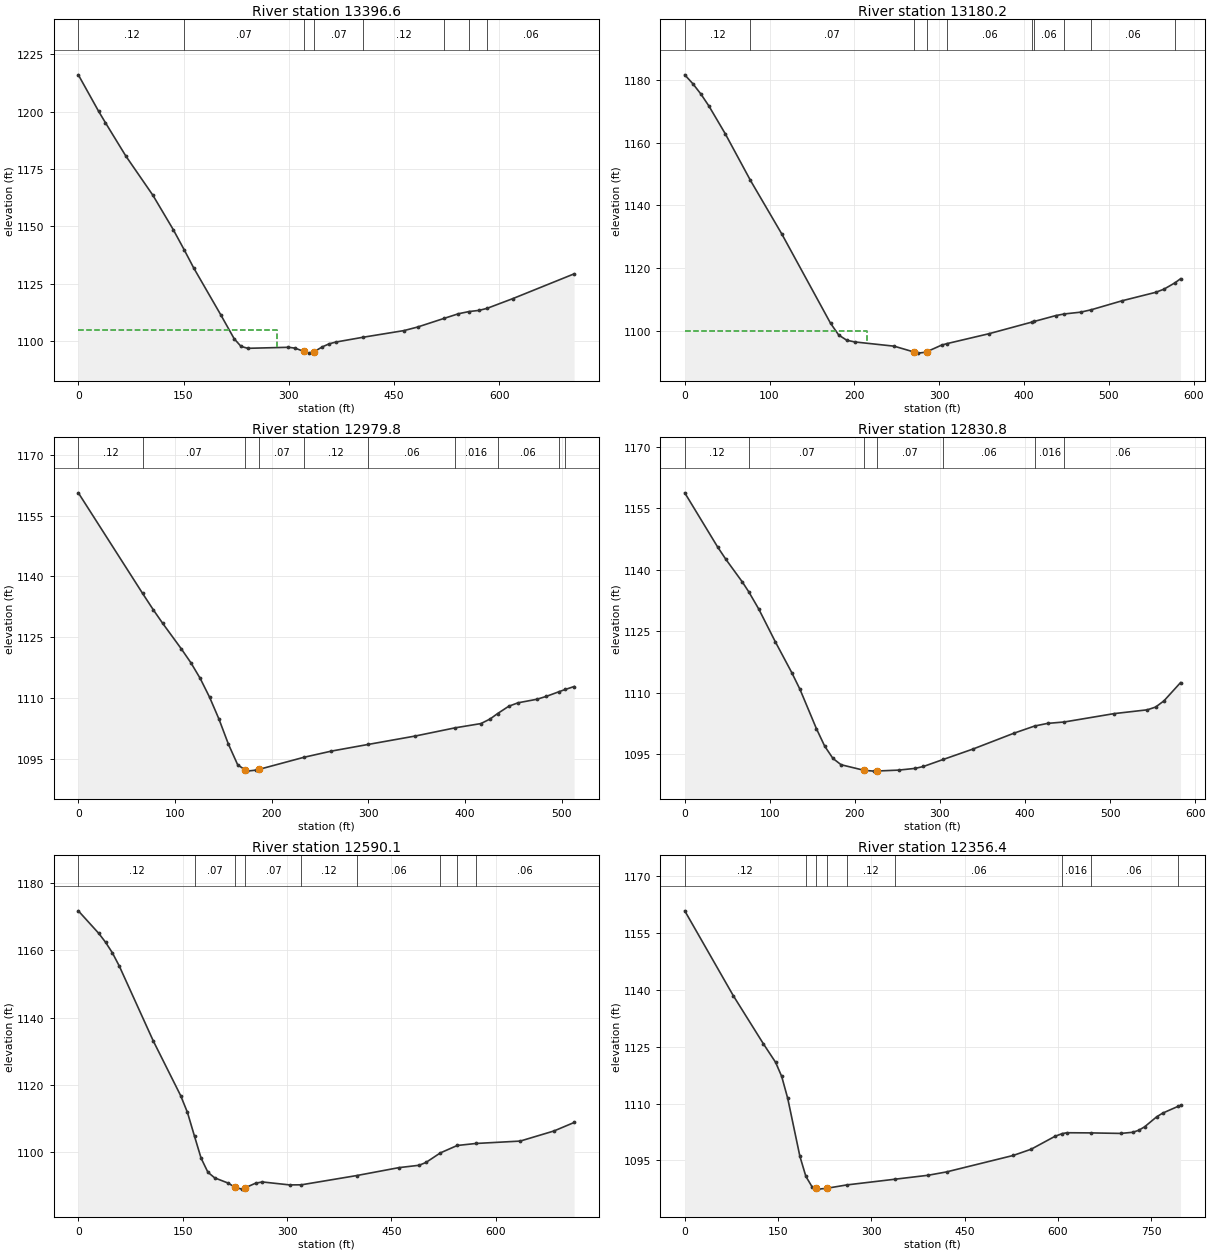
Type RM Length L Ch R = 1 ,13396.6 ,204,216.4,228.2
XS GIS Cut Line= 3
     1777844.125      252581.071     1778063.663      252825.496
     1778313.887      253109.137
#Sta/Elev= 30
       0 1216.06      29 1200.11    38.6 1195.19    67.6 1180.69   106.3  1163.5
   135.3 1148.53  151.271139.514   164.3 1131.89   202.9 1111.42   222.2 1100.88
   231.9 1097.57   241.6 1096.72   299.6 1097.17   309.2 1096.79   321.4 1095.36
   328.5 1094.62   336.4 1095.28   347.9 1097.36   357.6 1098.68   367.3 1099.46
  405.671101.539   464.3 1104.46   483.7 1106.01  521.631109.803   541.9  1111.8
  556.831112.756     571 1113.26  582.511114.135   619.5 1118.42   706.8 1129.21
#Mann= 8 ,-1 , 0
       0     .12       0  151.27     .07       0   321.4    .045       0
   336.4     .07       0  405.67     .12       0  521.63     .08       0
  556.83    .016       0  582.51     .06       0
#XS Ineff= 2 , 0
          283.18 1104.59
Permanent Ineff=
       F       F
Bank Sta=321.4,336.4
XS Rating Curve= 0 ,0
Exp/Cntr=0.3,0.1

Type RM Length L Ch R = 1 ,13180.2 ,205.4,200.3,194.9
XS GIS Cut Line= 4
     1777764.428      252710.183     1777887.041      252856.667
     1777922.848      253020.513     1778066.077      253195.209
#Sta/Elev= 30
       0 1181.52     9.6 1178.68    19.1 1175.39    28.6 1171.56    47.8 1162.77
   77.491147.953   114.6 1130.85   171.9 1102.56   181.5 1098.82     191 1097.16
   200.4 1096.62   246.9 1095.27  270.011093.441   274.9 1093.06   284.2 1093.34
  285.751093.548   302.8  1095.6  309.261096.088   358.7 1099.23   409.91102.969
  411.961103.125   437.3 1104.98  447.591105.515   466.8 1106.08  479.361106.848
   515.9 1109.72   555.2 1112.38     565 1113.38  577.871115.381   584.6  1116.7
#Mann= 10 ,-1 , 0
       0     .12       0   77.49     .07       0  270.01    .045       0
  285.75     .07       0  309.26     .06       0   409.9     .12       0
  411.96     .06       0  447.59    .016       0  479.36     .06       0
  577.87     .12       0
#XS Ineff= 2 , 0
          214.86 1100.07
Permanent Ineff=
       F       F
Bank Sta=270.01,285.75
XS Rating Curve= 0 ,0
Exp/Cntr=0.3,0.1

Type RM Length L Ch R = 1 ,12979.8 ,138.3,149.1,159.4
XS GIS Cut Line= 3
     1777633.134      252798.074     1777762.258      253069.341
     1777879.445      253246.207
#Sta/Elev= 30
       0 1160.59   66.411135.851    77.5 1131.81    87.2 1128.48   106.6 1122.15
   116.3  1118.8     126 1114.92   135.7 1110.29   145.4 1104.91   155.1 1098.78
   164.8 1093.64  172.371092.424   174.4  1092.1   184.1 1092.36  187.171092.554
  233.241095.507   261.7 1097.03  299.881098.678   348.6 1100.75  389.391102.748
   416.2  1103.8   425.8 1104.94  433.451106.263   445.1 1108.08   454.7 1108.92
     474 1109.78   483.7 1110.48  496.981111.645  503.551112.204   512.6 1112.92
#Mann= 10 ,-1 , 0
       0     .12       0   66.41     .07       0  172.37    .045       0
  187.17     .07       0  233.24     .12       0  299.88     .06       0
  389.39    .016       0  433.45     .06       0  496.98     .12       0
  503.55     .06       0
Bank Sta=172.37,187.17
XS Rating Curve= 0 ,0
Exp/Cntr=0.3,0.1

Type RM Length L Ch R = 1 ,12830.8 ,236.3,240.7,244.1
XS GIS Cut Line= 3
     1777585.391       252816.52     1777581.051      253164.827
     1777694.983      253369.905
#Sta/Elev= 30
       0 1158.72    38.7 1145.51    48.4  1142.5    67.7    1137   75.251134.603
    87.1 1130.37   106.4 1122.46   125.8 1114.92   135.5 1110.82   154.8 1101.26
   164.5 1097.01   174.2 1094.01   183.8 1092.47  210.94  1091.1   222.6 1090.91
  225.861090.934   251.6 1091.16   270.9 1091.58   280.6 1092.04  304.131093.771
   338.7 1096.28   387.4 1100.18  411.39  1101.9   426.5 1102.54  446.321102.888
   504.7 1104.92   543.8 1105.85   553.6 1106.52   563.4 1108.03   582.9 1112.48
#Mann= 7 ,-1 , 0
       0     .12       0   75.25     .07       0  210.94    .045       0
  225.86     .07       0  304.13     .06       0  411.39    .016       0
  446.32     .06       0
Bank Sta=210.94,225.86
XS Rating Curve= 0 ,0
Exp/Cntr=0.3,0.1

Type RM Length L Ch R = 1 ,12590.1 ,236.6,233.6,230.8
XS GIS Cut Line= 3
     1777400.164      252771.059     1777307.384      253232.429
     1777414.532      253449.662
#Sta/Elev= 30
       0 1171.74    29.4 1165.04    39.2 1162.39      49 1159.25    58.8 1155.38
   107.8 1133.08   147.1 1116.87   156.9 1111.86  167.111104.738   176.5 1098.29
   186.3  1094.1   196.1 1092.43   215.7 1090.86   225.2 1089.62   235.3 1089.09
   240.2 1089.51   254.9 1090.86   264.7 1091.22   303.9 1090.34   320.61090.369
  400.541093.132   460.8 1095.47     490 1096.18   499.7    1097  520.591099.859
  544.75 1102.05  571.381102.644   635.3 1103.36   683.8 1106.36   712.8 1108.88
#Mann= 9 ,-1 , 0
       0     .12       0  167.11     .07       0   225.2    .045       0
   240.2     .07       0   320.6     .12       0  400.54     .06       0
  520.59     .08       0  544.75    .016       0  571.38     .06       0
Bank Sta=225.2,240.2
XS Rating Curve= 0 ,0
Exp/Cntr=0.3,0.1

Type RM Length L Ch R = 1 ,12356.4 ,159.9,159.5,159.1
XS GIS Cut Line= 4
     1777214.298      252724.289     1777141.598      252872.943
     1777119.897      253196.294      1777246.85      253476.242
#Sta/Elev= 30
       0 1160.82    77.9 1138.48   126.5 1125.73     146 1120.88   155.8 1117.17
   165.5 1111.38   185.1 1096.08  194.691090.796   204.8    1088  211.19 1087.63
   214.6 1087.43  227.971087.645  260.631088.542   337.91090.045   391.4 1091.09
   420.8 1091.97     528 1096.31   556.8 1097.95   595.2 1101.36  606.971102.083
   614.4  1102.3  652.28 1102.26   700.9 1102.12   720.1 1102.42   729.7 1102.94
   739.3 1103.87   758.5 1106.48   768.1 1107.46  792.571109.228     797 1109.52
#Mann= 9 ,-1 , 0
       0     .12       0  194.69     .07       0  211.19    .045       0
  227.97     .07       0  260.63     .12       0   337.9     .06       0
  606.97    .016       0  652.28     .06       0  792.57    .016       0
Bank Sta=211.19,227.97
XS Rating Curve= 0 ,0
Exp/Cntr=0.3,0.1