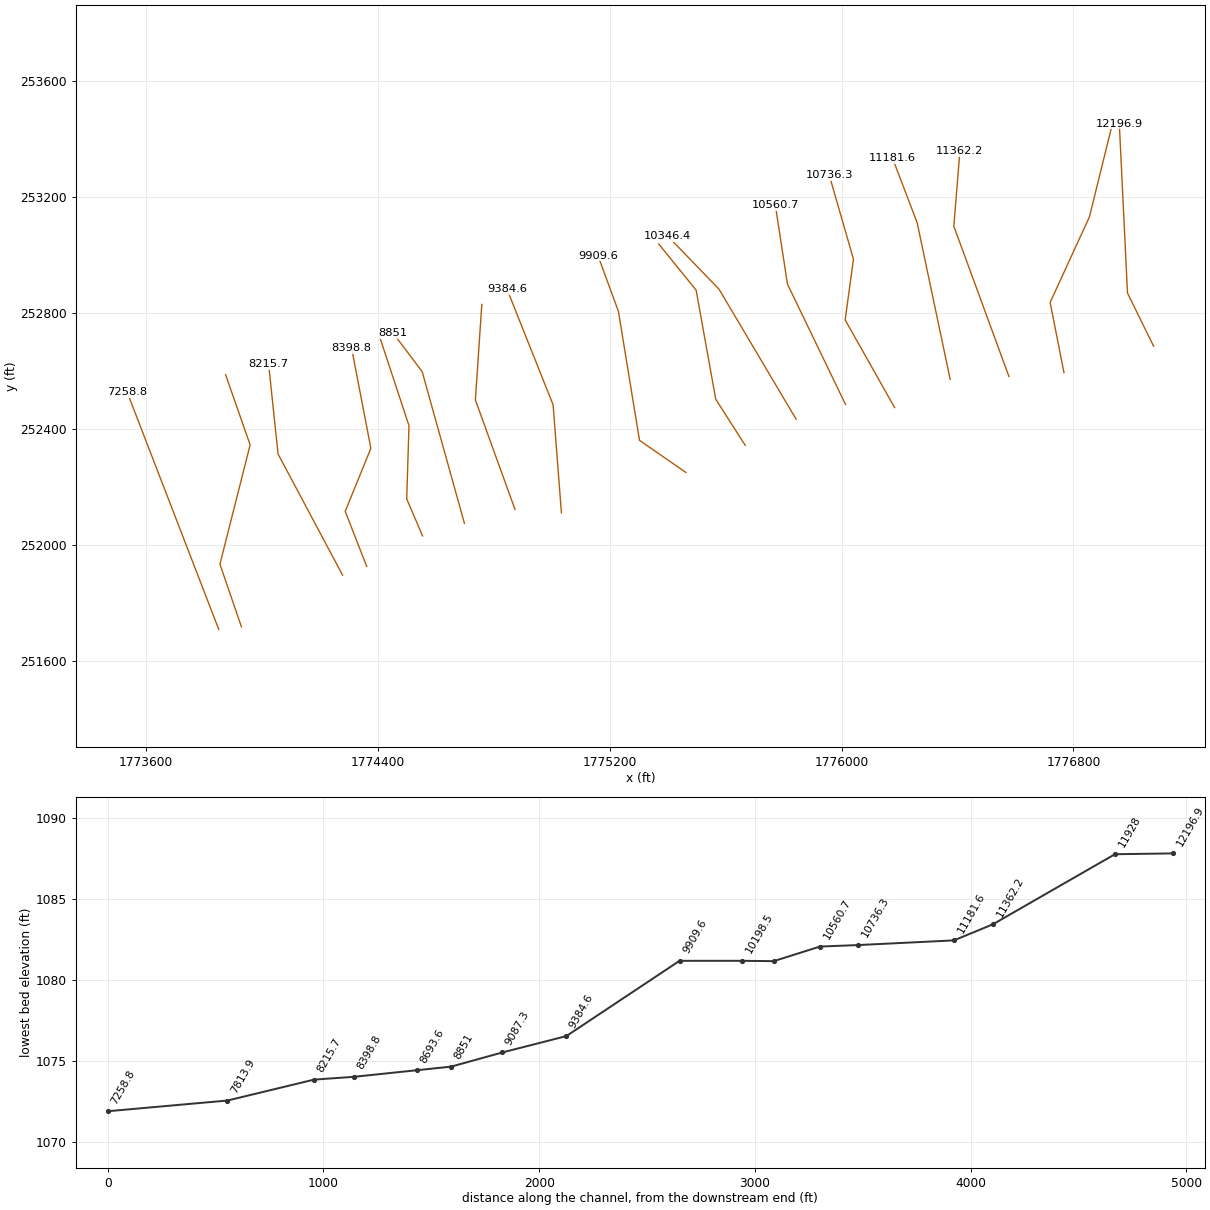
HEC-RAS study BUSHYFK1.prj: BUSHYFK1

--- BUSHYFK1.g01 (geometry) --- (continued)

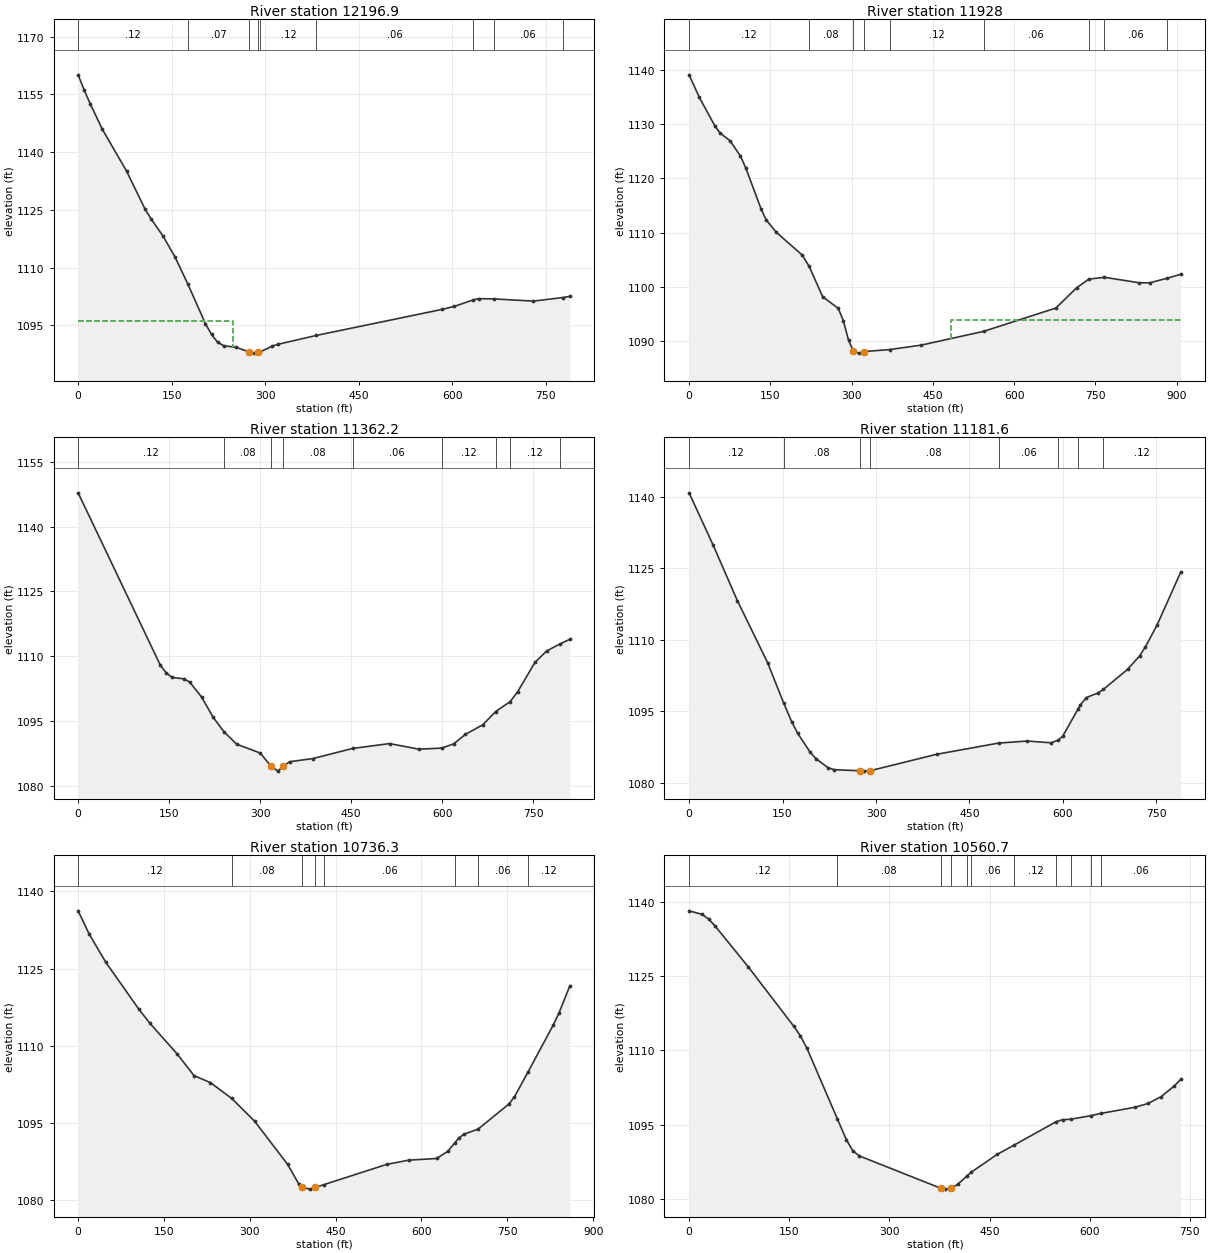
Type RM Length L Ch R = 1 ,12196.9 ,279.6,268.9,257.7
XS GIS Cut Line= 3
     1777076.494      252684.141     1776986.433      252867.518
     1776958.221      253451.285
#Sta/Elev= 30
       0 1160.08     9.7 1156.14    19.5 1152.51    38.9 1145.91    77.8 1135.05
     107 1125.32   116.7 1122.75   136.2 1118.19   155.7 1112.71  176.251105.647
   204.3 1095.43     214 1092.66   223.8 1090.64   233.5 1089.73     253 1089.34
   274.2 1088.13   282.2 1087.81   289.2 1088.05  292.281088.162   311.4 1089.64
   321.2 1090.13  382.24 1092.41   584.2 1099.18   603.7 1099.96  633.661101.637
   642.6 1101.96  666.511101.886   730.3 1101.32  777.551102.244   788.8 1102.56
#Mann= 9 ,-1 , 0
       0     .12       0  176.25     .07       0   274.2    .045       0
   289.2     .07       0  292.28     .12       0  382.24     .06       0
  633.66    .016       0  666.51     .06       0  777.55     .12       0
#XS Ineff= 2 , 0
           248.5 1096.11
Permanent Ineff=
       F       F
Bank Sta=274.2,289.2
XS Rating Curve= 0 ,0
Exp/Cntr=0.3,0.1

Type RM Length L Ch R = 1 ,11928   ,542.1,565.9,583.6
XS GIS Cut Line= 4
     1776767.249      252592.995     1776719.506      252834.966
      1776855.14      253130.105     1776935.746      253456.639
#Sta/Elev= 30
       0 1139.08      19 1134.91    47.4  1129.7    56.9 1128.38    75.9  1126.9
    94.9 1124.09   104.4 1121.98   132.8 1114.39   142.3 1112.32   161.3 1110.02
   208.7 1105.86  221.731103.751   246.6 1098.16   275.3 1096.02   284.8 1093.75
   294.4 1090.14  302.841088.198   313.5 1087.76   323.1 1088.05     3701088.416
   428.2 1089.23  543.941091.779   677.2 1096.08   715.6 1099.83  737.881101.404
  766.731101.745   830.9 1100.74   850.1 1100.72  882.251101.565   907.8  1102.3
#Mann= 9 ,-1 , 0
       0     .12       0  221.73     .08       0  302.84    .045       0
   323.1     .08       0     370     .12       0  543.94     .06       0
  737.88    .016       0  766.73     .06       0  882.25     .12       0
#XS Ineff= 2 , 0
                          482.97         1093.89
Permanent Ineff=
       F       F
Bank Sta=302.84,323.1
XS Rating Curve= 0 ,0
Exp/Cntr=0.3,0.1

Type RM Length L Ch R = 1 ,11362.2 ,181.5,180.6,177.7
XS GIS Cut Line= 3
     1776577.275      252579.758     1776387.171      253097.987
     1776408.004      253355.799
#Sta/Elev= 30
       0 1147.81   135.6 1107.92   145.3 1106.16     155 1105.11   174.3 1104.79
     184 1104.03   203.4  1100.6   222.7 1095.86  240.291092.554   261.5 1089.66
   300.2 1087.62  317.77  1084.6   329.3 1083.44   337.51084.514   348.6 1085.61
   387.4 1086.36  452.57 1088.69   513.3 1089.81   561.6 1088.52  598.99 1088.76
   619.1 1089.75   638.2 1091.93     667 1094.16  688.111097.204  712.271099.536
   724.4 1101.78   753.2 1108.62   772.3 1111.23  793.581112.814   810.6 1113.94
#Mann= 9 ,-1 , 0
       0     .12       0  240.29     .08       0  317.77    .045       0
   337.5     .08       0  452.57     .06       0  598.99     .12       0
  688.11    .016       0  712.27     .12       0  793.58     .06       0
Bank Sta=317.77,337.5
XS Rating Curve= 0 ,0
Exp/Cntr=0.3,0.1

Type RM Length L Ch R = 1 ,11181.6 ,447.5,445.3,437.2
XS GIS Cut Line= 3
     1776374.494      252569.866     1776260.562       253110.23
     1776175.926      253331.584
#Sta/Elev= 30
       0 1140.81    38.8  1129.8    77.5  1118.2     126 1105.21  151.581096.802
   164.7  1092.8   174.4 1090.36   193.8 1086.53   203.5 1085.08   222.8 1083.19
   232.5 1082.76   274.81082.516     281 1082.45   289.81082.514   397.2 1085.98
  496.68 1088.33   542.6 1088.76   580.7  1088.4  592.611088.952   599.6 1089.77
  624.03 1095.42   628.1 1096.38   637.6 1097.86   656.5 1098.87  664.821099.579
   703.9 1103.81   722.9 1106.59   732.4 1108.51   751.3 1113.14   789.2 1124.24
#Mann= 8 ,-1 , 0
       0     .12       0  151.58     .08       0   274.8    .045       0
   289.8     .08       0  496.68     .06       0  592.61     .12       0
  624.03    .016       0  664.82     .12       0
Bank Sta=274.8,289.8
XS Rating Curve= 0 ,0
Exp/Cntr=0.3,0.1

Type RM Length L Ch R = 1 ,10736.3 ,161.8,175.6,188.4
XS GIS Cut Line= 4
     1776182.744      252472.553     1776012.171      252774.636
     1776040.817      252984.272     1775957.483      253273.334
#Sta/Elev= 30
       0 1136.21    19.3  1131.7    48.2 1126.24     106 1117.12   125.3 1114.38
   173.5 1108.36   202.4 1104.22   231.3 1102.84  268.471099.765   308.4 1095.36
   366.2 1086.95   385.4 1083.19  391.83 1082.54   404.6 1082.16   414.2 1082.48
  429.151083.018   539.3 1086.97   577.9 1087.79   626.4 1088.11   645.8  1089.5
  658.59 1091.18   665.2  1092.1     675 1092.86  698.861093.815   752.6 1098.68
   762.3 1100.06  785.81 1104.84   830.2 1114.02   839.9 1116.28   859.3 1121.65
#Mann= 8 ,-1 , 0
       0     .12       0  268.47     .08       0  391.83    .045       0
   414.2     .12       0  429.15     .06       0  658.59    .016       0
  698.86     .06       0  785.81     .12       0
Bank Sta=391.83,414.2
XS Rating Curve= 0 ,0
Exp/Cntr=0.3,0.1

Type RM Length L Ch R = 1 ,10560.7 ,212,214.3,215.9
XS GIS Cut Line= 3
     1776013.473      252482.969     1775812.952      252898.334
     1775771.285      253170.469
#Sta/Elev= 30
       0 1138.13    19.6 1137.42    29.4 1136.47    39.2 1135.04    88.3  1126.9
     157 1114.85   166.8 1112.93   176.6 1110.42  221.981096.262   235.5 1092.06
   245.3 1089.78   255.2 1088.75   377.7 1082.21   382.7 1082.07   392.7 1082.25
   402.4 1083.04  416.461084.759  422.871085.504   461.2 1089.05  487.34 1090.98
  550.221095.681   559.6 1096.06   571.51096.148  601.461096.861  617.031097.329
   667.7 1098.56   687.4 1099.32     707  1100.7   726.7 1102.85   736.5  1104.2
#Mann= 11 ,-1 , 0
       0     .12       0  221.98     .08       0   377.7    .045       0
   392.7     .08       0  416.46     .12       0  422.87     .06       0
  487.34     .12       0  550.22    .016       0   571.5     .06       0
  601.46     .12       0  617.03     .06       0
Bank Sta=377.7,392.7
XS Rating Curve= 0 ,0
Exp/Cntr=0.3,0.1

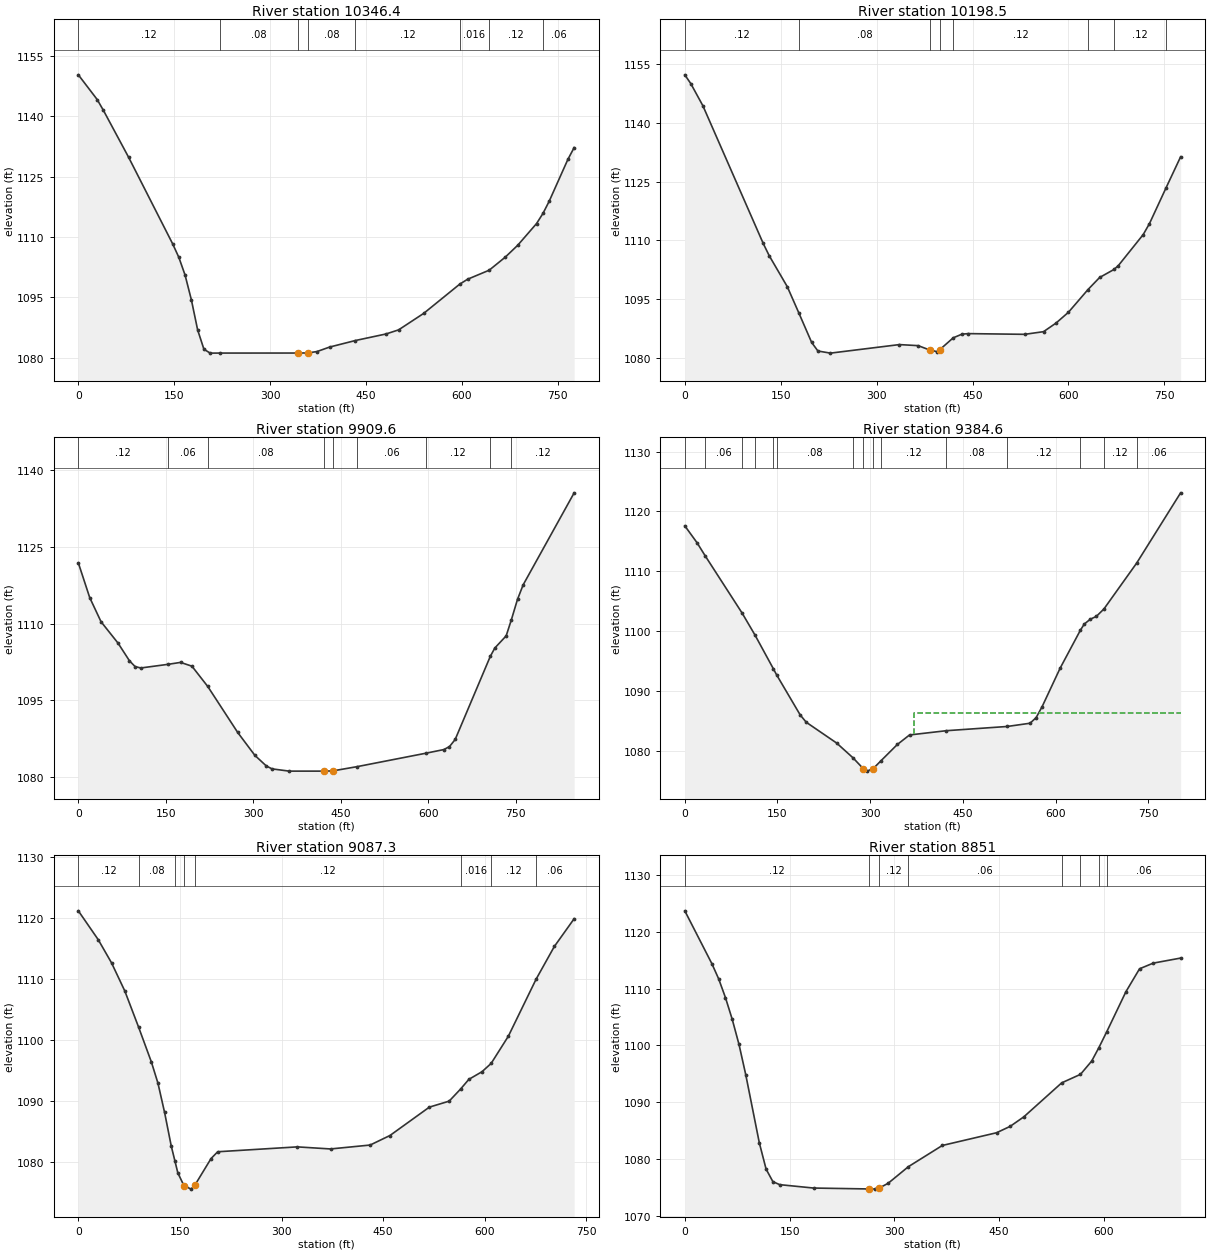
Type RM Length L Ch R = 1 ,10346.4 ,156.3,148,139.3
XS GIS Cut Line= 3
       1775842.9      252432.188     1775577.275      252880.105
     1775400.192      253063.699
#Sta/Elev= 30
       0 1150.34    29.5  1144.2    39.3 1141.49    78.6 1129.87   147.4 1108.39
   157.2    1105     167 1100.58   176.9  1094.4   186.7 1086.93   196.5 1082.14
   206.3 1081.17   221.11081.185   343.9 1081.19  359.331081.229   373.4 1081.56
     393 1082.67  433.39  1084.3   481.4 1085.93   501.1 1086.95   540.4 1091.05
  596.741098.311     609 1099.53  642.851101.782   667.9 1105.01   687.5 1107.98
     717 1113.38  727.061115.911   736.6 1118.88     766 1129.33   775.8 1132.26
#Mann= 8 ,-1 , 0
       0     .12       0   221.1     .08       0   343.9    .045       0
  359.33     .08       0  433.39     .12       0  596.74    .016       0
  642.85     .12       0  727.06     .06       0
Bank Sta=343.9,359.33
XS Rating Curve= 0 ,0
Exp/Cntr=0.3,0.1

Type RM Length L Ch R = 1 ,10198.5 ,289,288.8,288.3
XS GIS Cut Line= 4
     1775667.119      252342.344     1775565.556      252501.199
     1775497.848      252877.501     1775368.942      253036.355
#Sta/Elev= 30
       0 1152.24     9.4 1149.99    28.3 1144.34   122.6 1109.21     132 1106.07
   160.3 1098.15   178.71091.325   198.4 1083.92   208.2 1081.73   227.8 1081.19
   335.6 1083.37     365  1083.1  383.091081.983   394.4 1081.57  398.481082.028
  419.841085.101   433.6 1086.04   443.4 1086.17   531.7 1085.99   561.1 1086.67
   580.6 1088.86   600.1 1091.63  630.641097.424   648.8  1100.5  671.171102.541
     678 1103.52     717 1111.46   726.8 1114.27  752.811123.427   775.5 1131.32
#Mann= 8 ,-1 , 0
       0     .12       0   178.7     .08       0  383.09    .045       0
  398.48     .08       0  419.84     .12       0  630.64    .016       0
  671.17     .12       0  752.81     .06       0
Bank Sta=383.09,398.48
XS Rating Curve= 0 ,0
Exp/Cntr=0.3,0.1

Type RM Length L Ch R = 1 ,9909.6  ,526.1,525,523.5
XS GIS Cut Line= 4
     1775462.692      252248.594     1775302.535      252359.272
     1775229.619      252804.584     1775159.306       252995.99
#Sta/Elev= 30
       0 1121.89    19.5 1115.11    38.9 1110.39    68.1  1106.2    87.6 1102.76
    97.3 1101.62   107.1 1101.35  154.131102.068   175.2 1102.44   194.7  1101.7
  221.85 1097.73   273.2 1088.74   302.6 1084.27   322.2  1082.2     332 1081.63
   361.4 1081.19   420.3 1081.19  436.081081.235  477.861082.067  596.421084.708
   626.3  1085.4   636.1 1085.98   645.9 1087.38  706.11 1103.63   713.9 1105.26
   733.3 1107.63  742.211110.781   752.7 1114.76   762.4  1117.6   849.8 1135.58
#Mann= 9 ,-1 , 0
       0     .12       0  154.13     .06       0  221.85     .08       0
   420.3    .045       0  436.08     .08       0  477.86     .06       0
  596.42     .12       0  706.11    .016       0  742.21     .12       0
Bank Sta=420.3,436.08
XS Rating Curve= 0 ,0
Exp/Cntr=0.3,0.1

Type RM Length L Ch R = 1 ,9384.6  ,291.2,297.3,302.8
XS GIS Cut Line= 3
     1775033.004      252109.272     1775004.358      252481.667
     1774845.504      252880.105
#Sta/Elev= 30
       0 1117.58    19.7 1114.77    32.91112.578   92.761102.987  113.621099.306
  143.291093.679  148.421092.682   186.8 1085.94   196.6 1084.72   245.7 1081.25
  272.041078.791  289.061076.939   294.9 1076.55   304.7 1076.95  317.381078.274
     344 1081.01   363.7  1082.6  423.231083.312  521.711084.018   558.7 1084.56
   568.5 1085.49   578.2 1087.32   607.5 1093.79  640.351100.152   646.5 1101.15
   656.2 1101.96     666 1102.43  678.25 1103.67   731.21111.339   802.4  1123.1
#Mann= 15 ,-1 , 0
       0     .12       0    32.9     .06       0   92.76     .12       0
  113.62     .06       0  143.29     .12       0  148.42     .08       0
  272.04     .08       0  289.06    .045       0   304.7     .08       0
  317.38     .12       0  423.23     .08       0  521.71     .12       0
  640.35    .016       0  678.25     .12       0   731.2     .06       0
#XS Ineff= 2 , 0
                          371.52         1086.22
Permanent Ineff=
       F       F
Bank Sta=289.06,304.7
XS Rating Curve= 0 ,0
Exp/Cntr=0.3,0.1

Type RM Length L Ch R = 1 ,9087.3  ,238.8,236.3,233.7
XS GIS Cut Line= 3
     1774872.848       252120.99     1774736.129      252498.594
     1774758.265      252828.022
#Sta/Elev= 30
       0 1121.12    29.4 1116.39      49  1112.6    68.6 1107.99      891102.054
   107.7  1096.4   117.5  1092.9   127.3  1088.1   137.1 1082.62  142.411080.214
   146.9 1078.18  155.831076.121   166.5 1075.54   171.9 1076.17   195.9 1080.55
   205.7 1081.66   323.2 1082.46   372.2 1082.12   430.7 1082.76   459.9 1084.32
   518.1 1088.97   547.3 1089.95  564.171091.932   576.4 1093.52   595.8 1094.77
  609.261096.126   634.6 1100.57  675.61 1109.92   702.6 1115.29   731.8 1119.83
#Mann= 8 ,-1 , 0
       0     .12       0      89     .08       0  142.41     .12       0
  155.83    .045       0   171.9     .12       0  564.17    .016       0
  609.26     .12       0  675.61     .06       0
Bank Sta=155.83,171.9
XS Rating Curve= 0 ,0
Exp/Cntr=0.3,0.1

Type RM Length L Ch R = 1 ,8851    ,164.1,157.4,150.2
XS GIS Cut Line= 3
     1774698.369      252072.813     1774552.535      252596.251
     1774452.275      252729.063
#Sta/Elev= 30
       0 1123.74    38.8 1114.41    48.5 1111.74    58.2 1108.44    67.9 1104.61
    77.6 1100.18    87.3 1094.82   106.7 1082.82   116.4 1078.19   126.1 1075.99
   135.8 1075.46   184.4 1074.86   263.6  1074.7   271.7 1074.67   278.6 1074.88
   291.1  1075.7   320.11078.631   368.7 1082.37   446.3 1084.61   465.8 1085.74
   485.2  1087.4  539.581093.411  566.431094.907   582.5 1097.25  592.731099.607
  603.911102.383   631.5 1109.48     651 1113.52   670.6 1114.52   709.8 1115.41
#Mann= 8 ,-1 , 0
       0     .12       0   263.6    .045       0   278.6     .12       0
   320.1     .06       0  539.58    .016       0  566.43     .06       0
  592.73     .12       0  603.91     .06       0
Bank Sta=263.6,278.6
XS Rating Curve= 0 ,0
Exp/Cntr=0.3,0.1

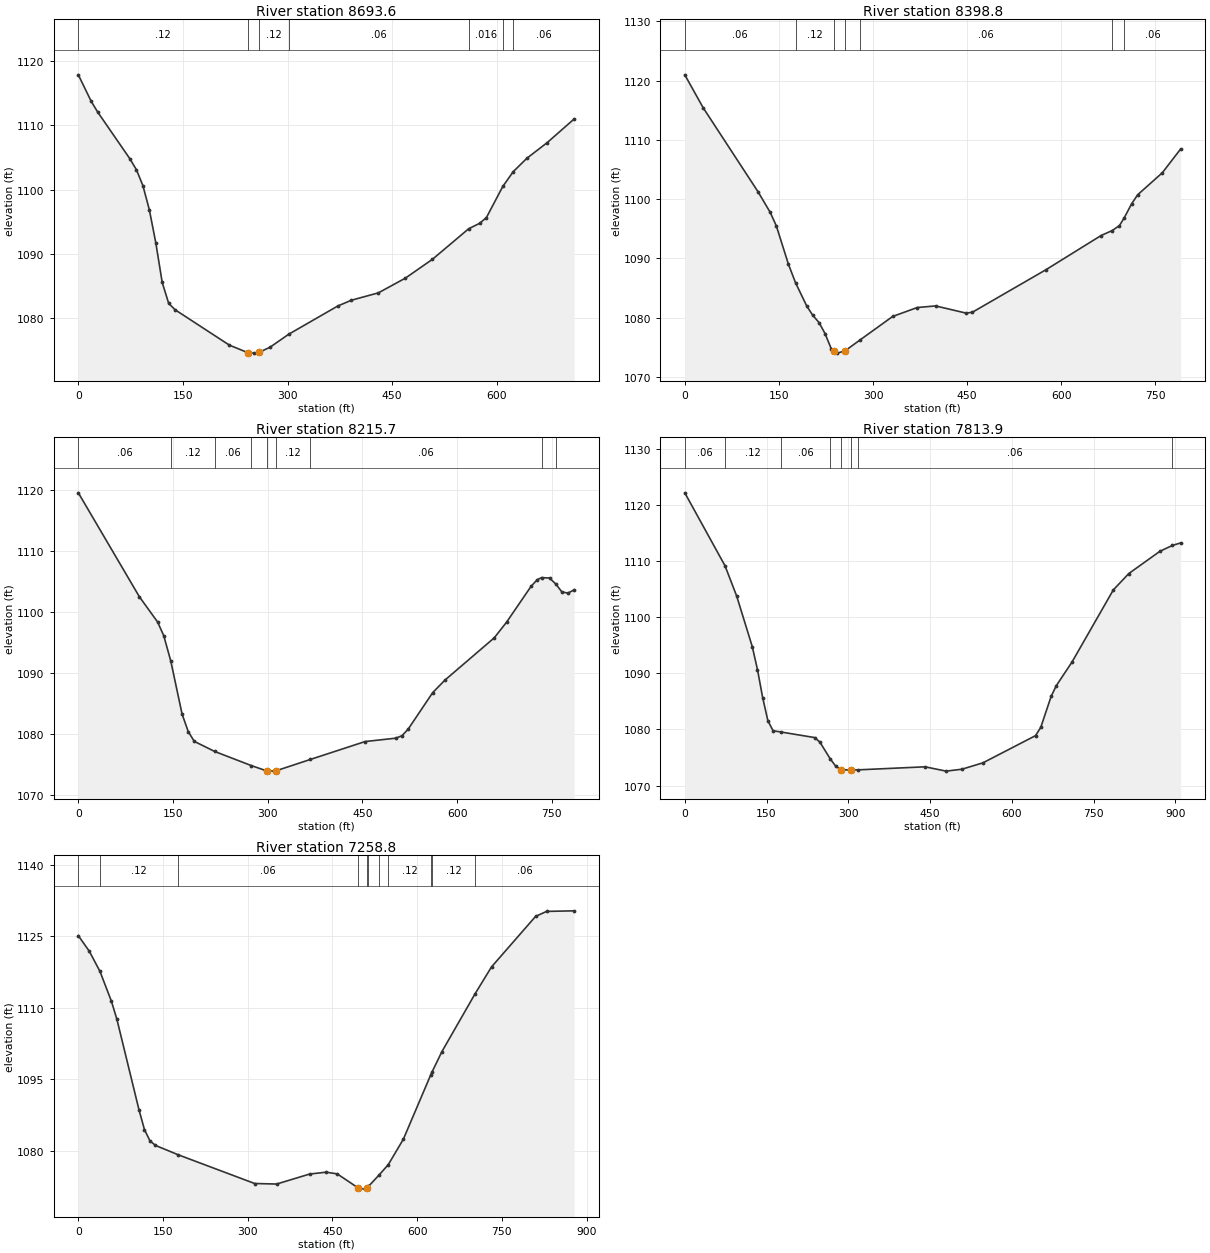
Type RM Length L Ch R = 1 ,8693.6  ,302.3,294.8,286.9
XS GIS Cut Line= 4
     1774553.838      252029.844      1774499.15      252157.449
     1774506.963      252410.053     1774406.702      252713.438
#Sta/Elev= 30
       0 1117.91    18.5 1113.76    27.8 1112.09      74 1104.79    83.3 1103.09
    92.6 1100.61   101.8 1096.86   111.1 1091.68   120.3 1085.48   129.6 1082.22
   138.8 1081.22   216.6  1075.7  243.061074.527   251.5 1074.45  258.921074.552
   274.9 1075.37  301.851077.409   372.1 1081.81   391.6 1082.71   430.3 1083.86
     469 1086.16   507.7 1089.09  559.931093.883   575.5 1094.72   585.2 1095.61
  608.791100.488  623.791102.795   643.3 1104.88   672.4 1107.32   711.1 1111.02
#Mann= 7 ,-1 , 0
       0     .12       0  243.06    .045       0  258.92     .12       0
  301.85     .06       0  559.93    .016       0  608.79     .12       0
  623.79     .06       0
Bank Sta=243.06,258.92
XS Rating Curve= 0 ,0
Exp/Cntr=0.3,0.1

Type RM Length L Ch R = 1 ,8398.8  ,162.9,183.1,203.1
XS GIS Cut Line= 4
     1774361.129      251924.376      1774286.91       252114.48
     1774375.452      252331.928     1774309.046       252676.98
#Sta/Elev= 30
       0 1120.97    29.2 1115.43   116.6 1101.27     136  1097.8   145.8 1095.52
   165.2 1089.02  176.541085.893   194.4 1081.97   204.1  1080.4   213.9  1079.2
   223.6 1077.32   233.4 1074.77  238.171074.414   243.2 1074.04  255.59 1074.44
  279.821076.303   331.2 1080.22   370.4 1081.73   399.7    1082   448.6 1080.78
   458.4 1080.94   575.5  1088.1   663.4 1093.87  680.94  1094.7   692.6 1095.53
  700.291096.848   712.2 1099.24   721.9 1100.76     761 1104.45   790.2 1108.46
#Mann= 7 ,-1 , 0
       0     .06       0  176.54     .12       0  238.17    .045       0
  255.59     .12       0  279.82     .06       0  680.94    .016       0
  700.29     .06       0
Bank Sta=238.17,255.59
XS Rating Curve= 0 ,0
Exp/Cntr=0.3,0.1

Type RM Length L Ch R = 1 ,8215.7  ,418.3,401.8,383.8
XS GIS Cut Line= 3
     1774277.796      251894.428      1774055.14      252312.397
     1774022.588      252622.292
#Sta/Elev= 30
       0 1119.48    96.6 1102.46   125.6  1098.3   135.3 1096.06  146.371091.928
   164.3 1083.22     174 1080.36   183.6 1078.75  215.831077.097  273.741074.787
   298.5  1073.9   309.3 1073.87   313.5 1073.94  367.351075.782   454.2 1078.72
   502.8 1079.27   512.5 1079.67   522.3 1080.75   561.2 1086.74   580.7  1088.8
   658.6 1095.71   678.1 1098.27     717 1104.16   726.8 1105.25  733.591105.579
   746.2 1105.52  756.361104.511   765.7 1103.24   775.4 1103.05   785.2 1103.58
#Mann= 9 ,-1 , 0
       0     .06       0  146.37     .12       0  215.83     .06       0
  273.74     .12       0   298.5    .045       0   313.5     .12       0
  367.35     .06       0  733.59    .016       0  756.36     .12       0
Bank Sta=298.5,313.5
XS Rating Curve= 0 ,0
Exp/Cntr=0.3,0.1

Type RM Length L Ch R = 1 ,7813.9  ,538.9,555.1,566.9
XS GIS Cut Line= 4
     1773928.838      251716.042     1773854.619      251932.188
     1773958.785      252343.647      1773874.15      252585.834
#Sta/Elev= 30
       0 1122.18   73.771109.177    95.2 1103.77   123.8 1094.76   133.3 1090.68
   142.8  1085.7   152.4 1081.57   161.9 1079.78  176.351079.553   238.2 1078.56
   247.8 1077.75  266.561074.801   276.8 1073.46   286.4 1072.85   305.7 1072.77
   317.11072.804   440.8 1073.35   479.3 1072.58   508.3 1072.92   546.9 1074.06
   643.3  1078.9     653 1080.39     672 1085.91   681.5 1087.82     710 1091.98
     786 1104.87   814.5  1107.8   871.5 1111.76   894.51112.809   909.5 1113.25
#Mann= 8 ,-1 , 0
       0     .06       0   73.77     .12       0  176.35     .06       0
  266.56     .12       0   286.4    .045       0   305.7     .12       0
   317.1     .06       0   894.5    .016       0
Bank Sta=286.4,305.7
XS Rating Curve= 0 ,0
Exp/Cntr=0.3,0.1

Type RM Length L Ch R = 1 ,7258.8  ,229.8,228.1,227.6
XS GIS Cut Line= 2
     1773850.713      251706.928     1773534.306      252525.938
#Sta/Elev= 30
       0 1125.15    19.5 1121.87   38.331117.646    58.5 1111.41    68.3 1107.59
   107.3 1088.63   117.1 1084.42   126.8 1082.07   136.6  1081.1  176.721079.139
   312.2  1073.1   351.2 1072.99   409.7 1075.09     439 1075.48   458.5 1075.12
   495.8 1072.15   507.3 1071.92   510.8 1072.23  513.631072.481  532.161074.836
  548.871077.066   575.6 1082.42  624.131095.948  626.08 1096.46   643.9 1100.82
  702.281112.895   731.7  1118.6   809.7  1129.2   829.2 1130.25     878 1130.37
#Mann= 11 ,-1 , 0
       0     .06       0   38.33     .12       0  176.72     .06       0
   495.8    .045       0   510.8     .06       0  513.63     .12       0
  532.16     .06       0  548.87     .12       0  624.13     .06       0
  626.08     .12       0  702.28     .06       0
Bank Sta=495.8,510.8
XS Rating Curve= 0 ,0
Exp/Cntr=0.3,0.1