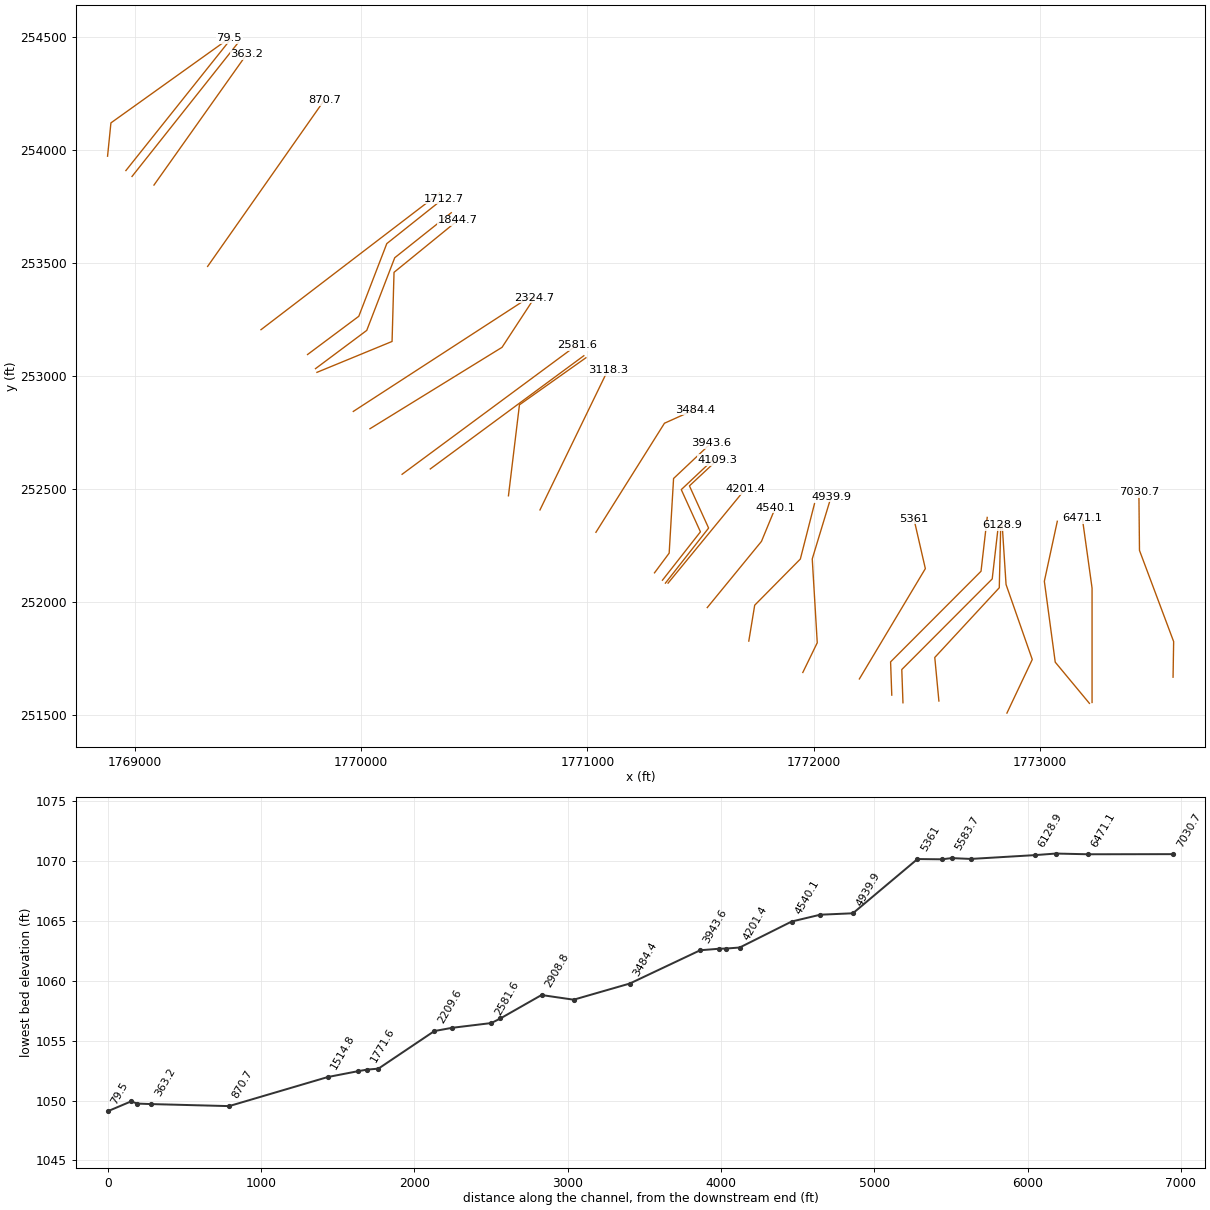
HEC-RAS study BUSHYFK1.prj: BUSHYFK1

--- BUSHYFK1.g01 (geometry) --- (continued)

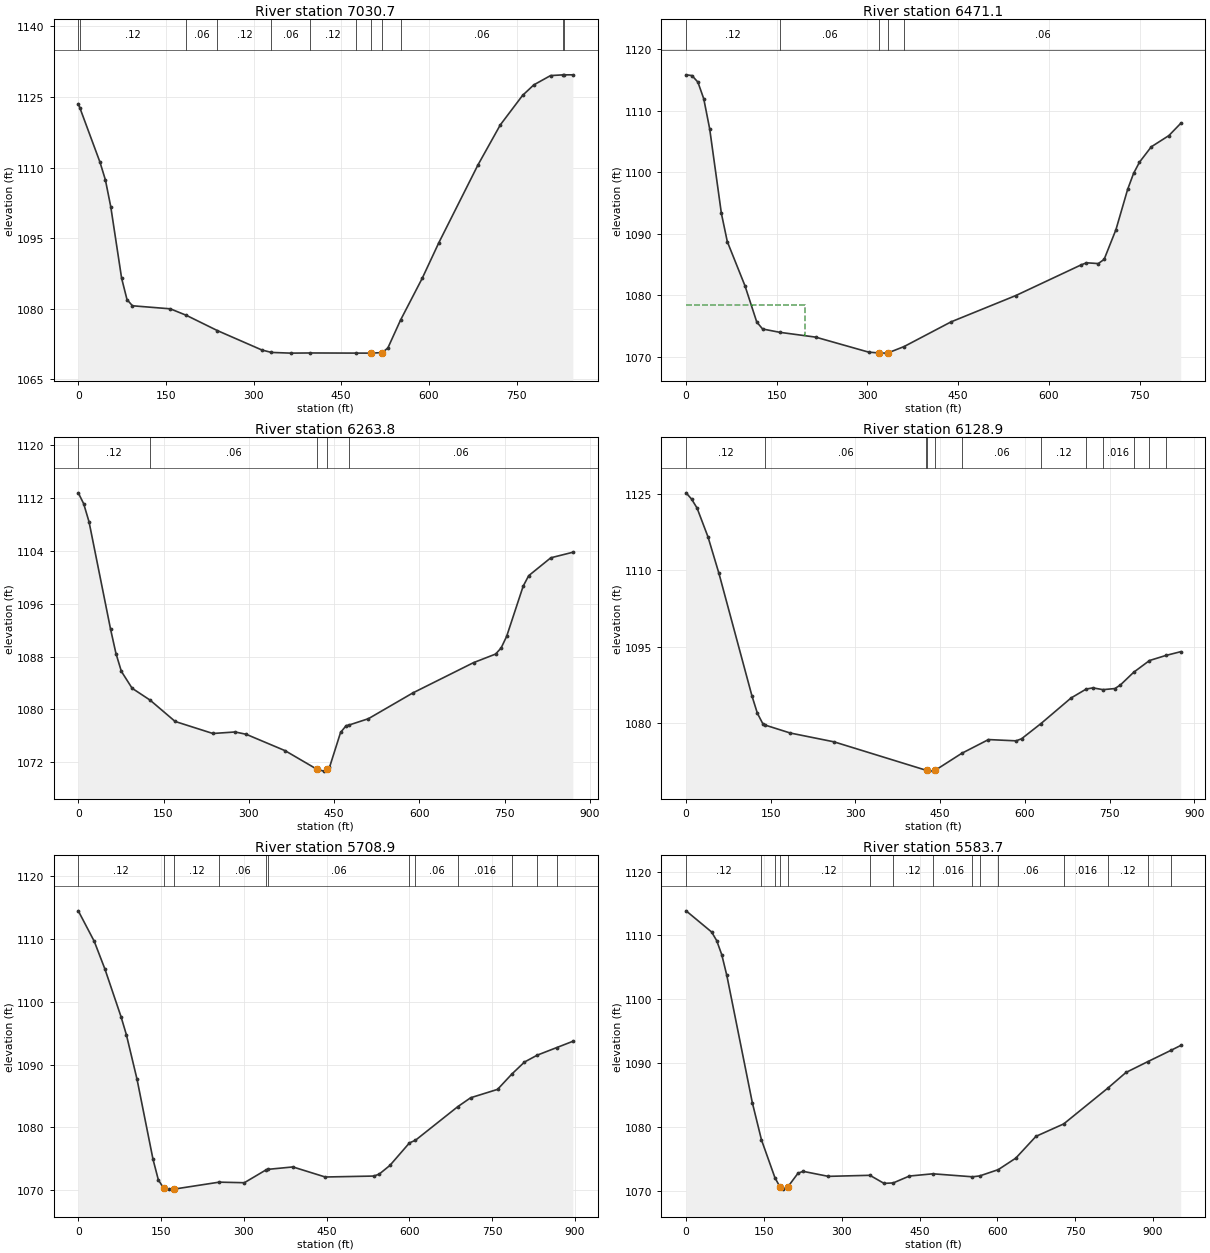
Type RM Length L Ch R = 1 ,7030.7  ,565.6,559.6,551.4
XS GIS Cut Line= 4
     1773588.994      251665.261     1773591.598      251822.813
     1773440.556      252226.459     1773437.952      252484.272
#Sta/Elev= 30
       0 1123.55    2.871122.646    37.1 1111.17    46.4  1107.4    55.6 1101.69
    74.2 1086.49    83.4 1081.97    92.7 1080.65   157.6    1080  184.921078.624
  238.22 1075.37   314.3 1071.25  330.64 1070.74   363.3 1070.59  396.691070.625
  475.121070.596   500.4 1070.59     520  1070.7   529.8 1071.68  551.461077.599
   588.6 1086.49   617.2 1094.09     684 1110.57   722.2 1119.07   760.4 1125.35
   779.5 1127.57   808.2 1129.55  830.161129.707  830.911129.706   846.4 1129.71
#Mann= 12 ,-1 , 0
       0     .06       0    2.87     .12       0  184.92     .06       0
  238.22     .12       0  330.64     .06       0  396.69     .12       0
  475.12     .06       0   500.4    .045       0     520     .12       0
  551.46     .06       0  830.16     .12       0  830.91     .06       0
Bank Sta=500.4,520
XS Rating Curve= 0 ,0
Exp/Cntr=0.3,0.1

Type RM Length L Ch R = 1 ,6471.1  ,204.3,207.4,210.4
XS GIS Cut Line= 3
     1773230.921      251553.282     1773230.921      252059.792
     1773187.952      252368.386
#Sta/Elev= 30
       0  1115.8     9.7 1115.68    19.5 1114.62    29.2 1111.91      39 1107.03
    58.4 1093.27    68.2 1088.69    97.4 1081.52   116.9 1075.63   126.6  1074.5
  155.091073.959   214.3 1073.18     302 1070.74   318.9 1070.61   331.2 1070.58
   333.9 1070.62  360.371071.638   438.3 1075.66   545.5 1079.94   652.6 1084.88
   662.3 1085.26   681.8 1085.13   691.5 1085.82     711 1090.64   730.4  1097.2
   740.2 1099.79   749.9  1101.6   769.4  1104.1   798.6 1105.93   818.1 1107.91
#Mann= 5 ,-1 , 0
       0     .12       0  155.09     .06       0   318.9    .045       0
   333.9     .12       0  360.37     .06       0
#XS Ineff= 2 , 0
          196.08 1078.45
Permanent Ineff=
       F       F
Bank Sta=318.9,333.9
XS Rating Curve= 0 ,0
Exp/Cntr=0.3,0.1

Type RM Length L Ch R = 1 ,6263.8  ,130.3,134.9,139.5
XS GIS Cut Line= 4
     1773219.202      251549.376      1773068.16      251731.667
     1773019.983       252089.74     1773077.275      252355.365
#Sta/Elev= 30
       0 1112.79     9.5 1111.14    18.9 1108.41    56.8 1092.14    66.3 1088.45
    75.8 1085.75    94.7 1083.19  126.321081.394   170.4 1078.16   236.7 1076.34
   275.8 1076.57   295.3 1076.22   363.7 1073.74  420.031070.909     432 1070.64
  436.761070.917   441.8 1071.21   461.3  1076.5   471.1 1077.53  476.291077.625
   510.2 1078.58   588.3 1082.48   695.1 1087.07   733.9 1088.37   743.6 1089.29
   753.3 1091.04   782.4 1098.65   792.1 1100.24     831 1102.95   869.8 1103.79
#Mann= 5 ,-1 , 0
       0     .12       0  126.32     .06       0  420.03    .045       0
  436.76     .12       0  476.29     .06       0
Bank Sta=420.03,436.76
XS Rating Curve= 0 ,0
Exp/Cntr=0.3,0.1

Type RM Length L Ch R = 1 ,6128.9  ,425.3,420,414.4
XS GIS Cut Line= 4
     1772854.619      251506.407     1772966.598      251743.386
     1772850.713      252075.417     1772833.785      252337.136
#Sta/Elev= 30
       0 1125.27     9.7 1124.04    19.4 1122.28    38.8  1116.6    58.2 1109.41
   116.5 1085.37   126.2 1081.91   135.9 1079.84  139.481079.589   184.4 1078.01
   262.1 1076.27  424.831070.691  426.121070.637   437.9 1070.51  440.781070.646
  488.16 1074.01   535.6 1076.72   584.5 1076.47   594.2 1076.88  628.571079.872
   681.8  1084.9  708.711086.662   720.6 1086.89  738.341086.542   759.5 1086.76
   769.2 1087.46  792.811089.971  820.741092.271  849.631093.266     876 1094.01
#Mann= 12 ,-1 , 0
       0     .12       0  139.48     .06       0  424.83     .12       0
  426.12    .045       0  440.78     .12       0  488.16     .06       0
  628.57     .12       0  708.71     .06       0  738.34    .016       0
  792.81     .12       0  820.74     .06       0  849.63     .12       0
Bank Sta=426.12,440.78
XS Rating Curve= 0 ,0
Exp/Cntr=0.3,0.1

Type RM Length L Ch R = 1 ,5708.9  ,145.2,125.1,105.1
XS GIS Cut Line= 4
     1772553.838      251559.792     1772535.608      251752.501
     1772820.765      252061.094     1772827.275      252343.647
#Sta/Elev= 30
       0 1114.47      29 1109.61    48.4 1105.18    77.4 1097.65    87.1 1094.79
   106.5 1087.67   135.5 1074.92   145.2 1071.64   154.8 1070.35   164.2 1070.19
   174.2  1070.2  255.44  1071.3     301 1071.21   339.81073.226  343.071073.331
     389 1073.72   447.6 1072.12   535.6 1072.27   545.3 1072.57   564.9 1073.97
  600.27 1077.55  611.131077.967  687.991083.324   711.2 1084.73   759.9 1086.06
  786.011088.517   808.7 1090.41  831.881091.508  867.511092.724   896.4 1093.71
#Mann= 12 ,-1 , 0
       0     .12       0   154.8    .045       0   174.2     .12       0
  255.44     .06       0   339.8     .12       0  343.07     .06       0
  600.27     .12       0  611.13     .06       0  687.99    .016       0
  786.01     .12       0  831.88     .06       0  867.51     .12       0
Bank Sta=154.8,174.2
XS Rating Curve= 0 ,0
Exp/Cntr=0.3,0.1

Type RM Length L Ch R = 1 ,5583.7  ,62,61.8,62.8
XS GIS Cut Line= 4
     1772394.983       251551.98     1772389.775      251699.115
     1772789.515      252100.157     1772816.858      252338.438
#Sta/Elev= 30
       0 1113.85    49.1 1110.54    58.9  1109.2    68.7 1106.99    78.5 1103.73
   127.6 1083.82  145.28 1077.98  171.241072.046  181.051070.593   186.3 1070.26
     196  1070.6   215.6 1072.74   225.3 1073.05   274.1 1072.26  354.281072.426
   381.5 1071.16  399.221071.233   430.4 1072.31  475.771072.661  551.981072.192
  565.781072.326  601.691073.313   635.4 1075.11   674.4 1078.53  727.861080.476
  812.911086.084   847.8 1088.53  889.771090.224  934.931092.013   953.3 1092.76
#Mann= 15 ,-1 , 0
       0     .12       0  145.28    .016       0  171.24     .12       0
  181.05    .045       0     196     .12       0  354.28     .06       0
  399.22     .12       0  475.77    .016       0  551.98     .06       0
  565.78     .12       0  601.69     .06       0  727.86    .016       0
  812.91     .12       0  889.77     .06       0  934.93     .12       0
Bank Sta=181.05,196
XS Rating Curve= 0 ,0
Exp/Cntr=0.3,0.1

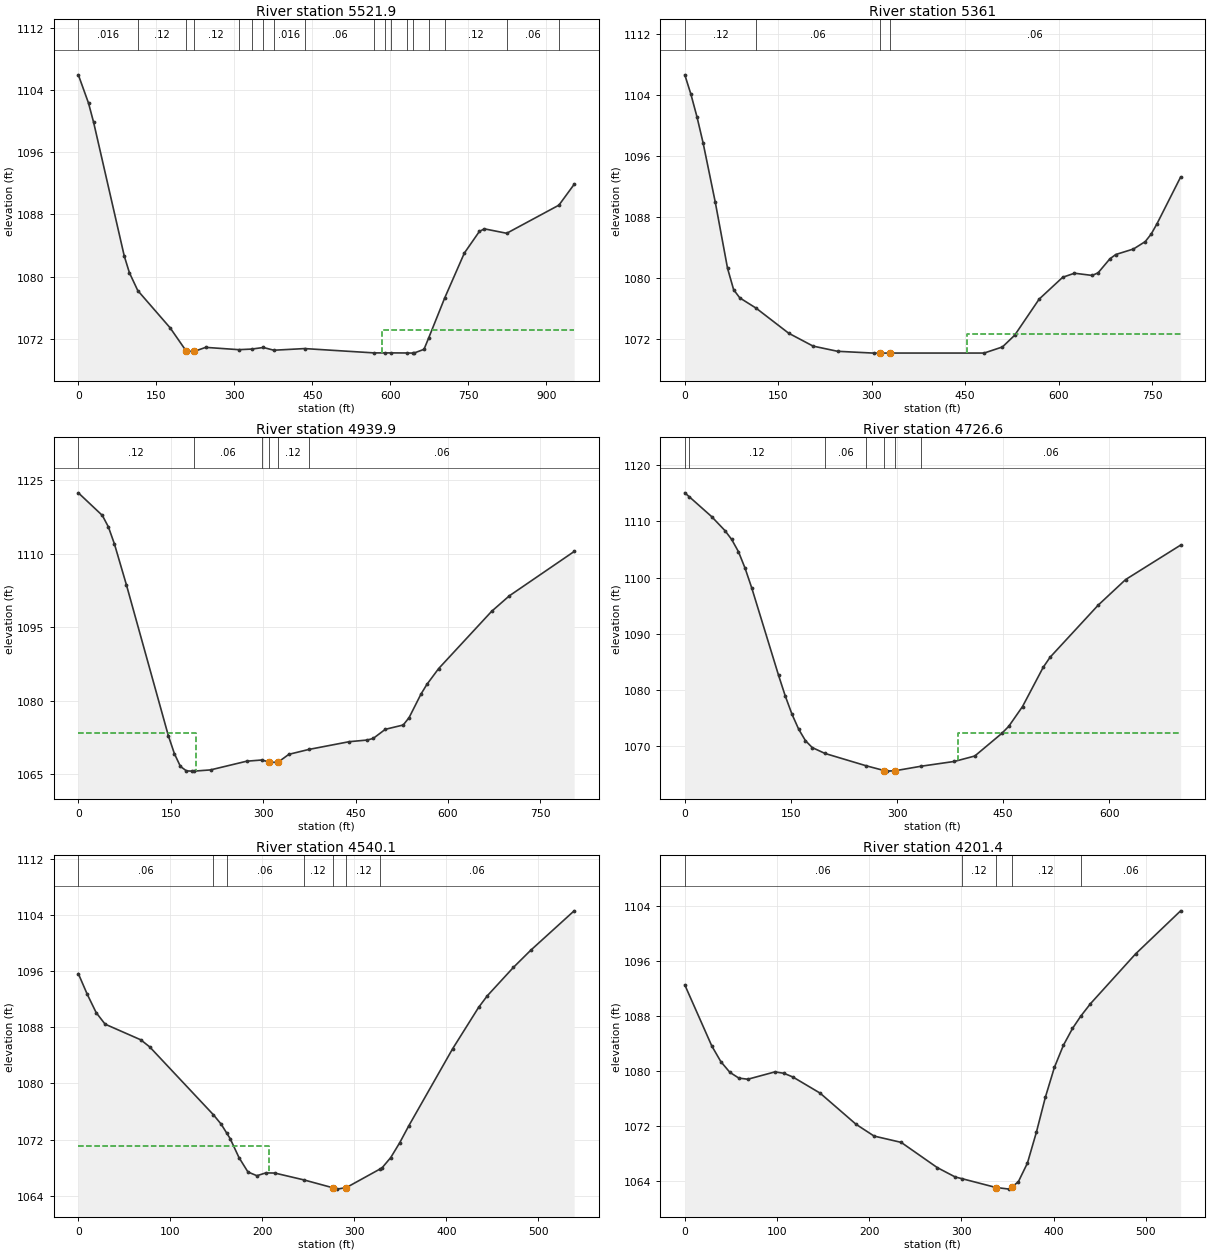
Type RM Length L Ch R = 1 ,5521.9  ,146.6,160.9,165
XS GIS Cut Line= 4
     1772345.504      251585.834     1772340.296      251732.969
     1772740.035      252134.011     1772767.379      252372.292
#Sta/Elev= 30
       0 1105.92    19.6 1102.28    29.4 1099.81    88.3 1082.64    98.2 1080.49
  114.311078.195   176.5 1073.41   207.3 1070.44   222.3 1070.37   244.8  1070.9
  308.411070.605  333.34 1070.68  355.781070.885  375.891070.533  435.071070.745
  568.51 1070.19  588.67 1070.19  601.96 1070.19  631.22 1070.18  642.991070.164
   645.1 1070.16   664.6 1070.65  673.771072.138  704.411077.251   742.2 1083.02
     771 1085.79   780.6 1086.13  823.61 1085.56  924.011089.175   953.3 1091.85
#Mann= 18 ,-1 , 0
       0    .016       0  114.31     .12       0   207.3    .045       0
   222.3     .12       0  308.41     .06       0  333.34    .016       0
  355.78     .12       0  375.89    .016       0  435.07     .06       0
  568.51     .12       0  588.67    .016       0  601.96     .12       0
  631.22    .016       0  642.99     .06       0  673.77    .016       0
  704.41     .12       0  823.61     .06       0  924.01     .12       0
#XS Ineff= 2 , 0
                          583.08         1073.18
Permanent Ineff=
       F       F
Bank Sta=207.3,222.3
XS Rating Curve= 0 ,0
Exp/Cntr=0.3,0.1

Type RM Length L Ch R = 1 ,5361    ,412.2,421.1,428.3
XS GIS Cut Line= 3
     1772202.275      251657.449     1772493.942       252145.73
      1772443.16      252367.084
#Sta/Elev= 30
       0 1106.61     9.8 1104.07    19.6 1101.09    29.4 1097.69      49 1089.91
    68.6 1081.29    78.4 1078.48    88.3 1077.41   114.31076.077   166.7 1072.79
   205.9  1071.1   245.2 1070.42     304 1070.18   313.7 1070.18   328.7 1070.19
   480.5 1070.19   509.9 1070.99   529.5 1072.52   568.8 1077.25   606.6 1080.11
   625.5 1080.64   653.9 1080.35   663.4 1080.69   682.3 1082.52   691.8 1083.09
   720.2 1083.81   739.1 1084.78   748.6 1085.76     758 1087.12   795.9 1093.23
#Mann= 4 ,-1 , 0
       0     .12       0   114.3     .06       0   313.7    .045       0
   328.7     .06       0
#XS Ineff= 2 , 0
                          453.25         1072.64
Permanent Ineff=
       F       F
Bank Sta=313.7,328.7
XS Rating Curve= 0 ,0
Exp/Cntr=0.3,0.1

Type RM Length L Ch R = 1 ,4939.9  ,232.5,213.3,193.3
XS GIS Cut Line= 4
     1771952.275      251686.094     1772016.077      251817.605
     1771993.942      252188.699     1772077.275      252463.438
#Sta/Elev= 30
       0 1122.48      39 1117.86    48.7 1115.55    58.5 1112.08      78 1103.72
   146.2 1072.87     156 1069.21   165.7 1066.62   175.5  1065.7   185.3 1065.65
  188.281065.653   214.6  1065.9   273.4 1067.68  298.421067.926  310.331067.458
  323.951067.442   341.8 1069.08   374.21070.077   439.7 1071.66     469    1072
   478.8 1072.33   498.4 1074.19   527.5 1075.07   537.1  1076.6   556.2 1081.36
   565.8 1083.34   584.9 1086.58     671 1098.28   699.8 1101.45     805  1110.5
#Mann= 6 ,-1 , 0
       0     .12       0  188.28     .06       0  298.42     .12       0
  310.33    .045       0  323.95     .12       0   374.2     .06       0
#XS Ineff= 2 , 0
          190.92 1073.36
Permanent Ineff=
       F       F
Bank Sta=310.33,323.95
XS Rating Curve= 0 ,0
Exp/Cntr=0.3,0.1

Type RM Length L Ch R = 1 ,4726.6  ,183.7,186.5,188.4
XS GIS Cut Line= 4
     1771713.473      251824.897     1771739.515      251983.751
     1771941.338      252188.178     1772003.838      252432.969
#Sta/Elev= 30
       0 1115.09    5.961114.431    37.9 1110.86    56.8 1108.36    66.3 1106.78
    75.8 1104.62    85.2 1101.67    94.7 1098.13   132.6 1082.57     142 1078.92
   151.5 1075.67     161 1072.99   170.6 1070.95   180.1 1069.73   198.11068.682
  256.741066.469  281.971065.631   285.5 1065.53  297.211065.597  334.111066.404
   381.2 1067.26   409.9 1068.22   448.2 1072.26     458 1073.52   477.4 1077.03
   506.6 1084.01   516.3  1085.8   584.3 1095.08   623.2 1099.65   700.9 1105.78
#Mann= 7 ,-1 , 0
       0     .06       0    5.96     .12       0   198.1     .06       0
  256.74     .12       0  281.97    .045       0  297.21     .12       0
  334.11     .06       0
#XS Ineff= 2 , 0
                          385.55         1072.26
Permanent Ineff=
       F       F
Bank Sta=281.97,297.21
XS Rating Curve= 0 ,0
Exp/Cntr=0.3,0.1

Type RM Length L Ch R = 1 ,4540.1  ,338,338.7,337.5
XS GIS Cut Line= 3
     1771529.879      251973.334     1771769.463      252266.303
      1771830.66       252414.74
#Sta/Elev= 30
       0 1095.63     9.7 1092.69    19.4 1090.08    29.1 1088.44    67.9 1086.21
    77.6  1085.2  146.86 1075.54   155.3  1074.2  161.091072.982     165 1072.16
   174.7 1069.44   184.4  1067.4   194.1 1066.87   203.8 1067.27   213.5 1067.25
  245.171066.275   276.5 1065.16   281.4 1064.96   291.5 1065.19  328.33 1067.85
   329.9 1067.95   339.6 1069.45   349.4 1071.57     359 1073.92   406.8 1084.92
   435.1 1090.82   444.6 1092.48   472.9 1096.51   491.8 1098.96     539 1104.57
#Mann= 7 ,-1 , 0
       0     .06       0  146.86     .12       0  161.09     .06       0
  245.17     .12       0   276.5    .045       0   291.5     .12       0
  328.33     .06       0
#XS Ineff= 2 , 0
          206.81 1071.15
Permanent Ineff=
       F       F
Bank Sta=276.5,291.5
XS Rating Curve= 0 ,0
Exp/Cntr=0.3,0.1

Type RM Length L Ch R = 1 ,4201.4  ,66.9,92.1,117.6
XS GIS Cut Line= 2
     1771356.598      252081.581      1771697.57      252497.466
#Sta/Elev= 30
       0 1092.54    29.3 1083.64    39.1 1081.36    48.9  1079.8    58.7 1078.96
    68.4  1078.8    97.8 1079.87   107.6 1079.66   117.3 1079.12   146.7 1076.78
   185.8 1072.23   205.3 1070.52   234.7  1069.6   273.8 1065.93   293.3 1064.56
  300.321064.324  337.591063.026     352 1062.79   354.91063.108   361.8 1063.87
   371.6 1066.57   381.4  1071.1   391.1 1076.18   400.9 1080.53   410.7 1083.76
   420.5 1086.19  429.45 1087.98     440  1089.8   488.9 1097.05   537.8 1103.33
#Mann= 5 ,-1 , 0
       0     .06       0  300.32     .12       0  337.59    .045       0
   354.9     .12       0  429.45     .06       0
Bank Sta=337.59,354.9
XS Rating Curve= 0 ,0
Exp/Cntr=0.3,0.1

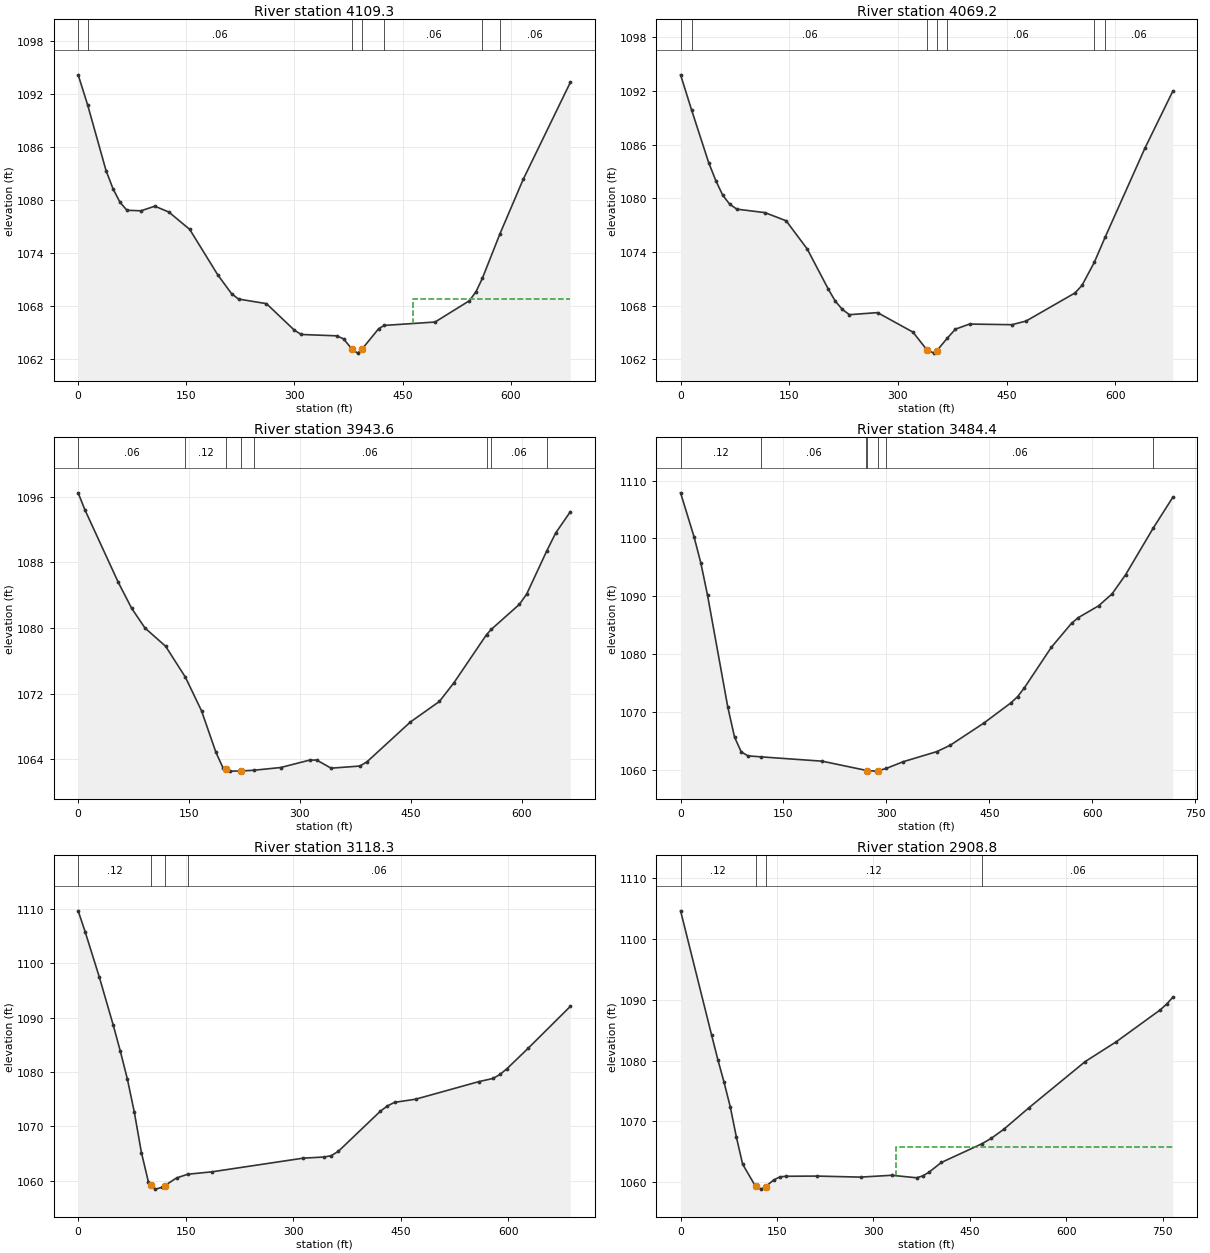
Type RM Length L Ch R = 1 ,4109.3  ,40.1,40.1,40.1
XS GIS Cut Line= 4
     1771344.879      252081.581     1771535.765      252325.244
     1771451.042      252512.049     1771573.959      252626.633
#Sta/Elev= 30
       0  1094.2   13.021090.836    38.7 1083.36    48.4  1081.3      58 1079.78
    67.7 1078.87    87.1 1078.81   106.4 1079.33   125.8 1078.67   154.8  1076.7
   193.5 1071.58   212.8 1069.43   222.5 1068.82   261.2  1068.3   299.9  1065.3
   309.5 1064.81   358.4 1064.66   368.1 1064.32  380.021063.139   387.7  1062.7
  394.011063.179     417 1065.48  424.681065.836   495.1 1066.22   542.7 1068.63
     552 1069.67  560.66 1071.16  585.021076.189   617.3 1082.36   682.7 1093.34
#Mann= 7 ,-1 , 0
       0     .12       0   13.02     .06       0  380.02    .045       0
  394.01     .12       0  424.68     .06       0  560.66     .12       0
  585.02     .06       0
#XS Ineff= 2 , 0
                           464.5         1068.81
Permanent Ineff=
       F       F
Bank Sta=380.02,394.01
XS Rating Curve= 0 ,0
Exp/Cntr=0.3,0.1

Type RM Length L Ch R = 1 ,4069.2  ,136.7,125.7,114.2
XS GIS Cut Line= 4
     1771331.858      252094.601     1771499.654      252308.577
     1771414.931      252495.383     1771562.154      252634.272
#Sta/Elev= 30
       0 1093.81   15.131089.899    38.8 1083.99    48.6 1081.99    58.3 1080.33
      68 1079.33    77.7 1078.79   116.5  1078.4   145.7 1077.49   174.8 1074.34
   203.9 1069.85   213.6  1068.5   223.4 1067.57   233.1 1066.99   271.9 1067.22
   320.8 1065.04   340.3 1063.03   350.1 1062.69   353.9 1062.97  368.061064.354
   379.4 1065.37   398.9 1065.94   457.5 1065.87     477 1066.28   544.5 1069.42
   554.1 1070.26  571.031072.825  586.161075.671   640.9 1085.59   679.4 1091.97
#Mann= 7 ,-1 , 0
       0     .12       0   15.13     .06       0   340.3    .045       0
   353.9     .12       0  368.06     .06       0  571.03     .12       0
  586.16     .06       0
Bank Sta=340.3,353.9
XS Rating Curve= 0 ,0
Exp/Cntr=0.3,0.1

Type RM Length L Ch R = 1 ,3943.6  ,468,459.2,432.2
XS GIS Cut Line= 4
     1771296.702      252127.153     1771361.427      252214.262
     1771380.904      252544.688       1771545.4       252700.07
#Sta/Elev= 30
       0 1096.47       9 1094.43    54.3 1085.56    72.4  1082.4    90.4    1080
   118.3 1077.78  145.13    1074   166.9 1069.91   186.4 1064.85   196.1 1062.93
  200.461062.765   205.9 1062.56  219.911062.578  237.361062.664     274    1063
     313  1063.9   322.7 1063.91   342.2 1062.92   381.1 1063.18   390.8  1063.7
   449.4 1068.54   488.7 1071.05   508.4 1073.33  552.441079.188  558.721079.818
   596.9 1082.88   606.8 1084.14  634.031089.409   646.1 1091.59   665.8 1094.16
#Mann= 8 ,-1 , 0
       0     .06       0  145.13     .12       0  200.46    .045       0
  219.91     .12       0  237.36     .06       0  552.44    .016       0
  558.72     .06       0  634.03     .12       0
Bank Sta=200.46,219.91
XS Rating Curve= 0 ,0
Exp/Cntr=0.3,0.1

Type RM Length L Ch R = 1 ,3484.4  ,363.5,366.1,368.6
XS GIS Cut Line= 3
     1771037.674      252306.581     1771340.647      252789.301
     1771475.088       252849.81
#Sta/Elev= 30
       0 1107.89    19.6  1100.3    29.5 1095.77    39.3 1090.18    68.8 1070.87
    78.6 1065.68    88.4  1063.1    98.3 1062.42  117.771062.241   206.4  1061.5
  270.661059.906  272.061059.879     285 1059.78  287.931059.851  299.681060.239
   324.3  1061.4   373.4 1063.15     393 1064.25   442.2  1068.1   481.5 1071.58
   491.3 1072.66   501.1 1074.18   540.4 1081.18   569.9 1085.34   579.8 1086.32
   609.2 1088.35   628.9 1090.41   648.6 1093.72  688.771101.758   717.4  1107.1
#Mann= 7 ,-1 , 0
       0     .12       0  117.77     .06       0  270.66     .12       0
  272.06    .045       0  287.93     .12       0  299.68     .06       0
  688.77    .016       0
Bank Sta=272.06,287.93
XS Rating Curve= 0 ,0
Exp/Cntr=0.3,0.1

Type RM Length L Ch R = 1 ,3118.3  ,201.1,209.5,217.2
XS GIS Cut Line= 2
     1770790.279      252405.539     1771089.671      253022.987
#Sta/Elev= 30
       0 1109.65     9.8 1105.78    29.4 1097.51      49 1088.58    58.8 1083.82
    68.6 1078.71    78.4 1072.54    88.2 1065.17      98 1059.73  101.961059.205
   107.8 1058.43   117.6 1058.79  121.021059.094   137.2 1060.49  152.921061.173
   186.3 1061.61   313.7 1064.13   343.1 1064.34   352.9 1064.59   362.7 1065.38
   421.5 1072.79   431.3 1073.75   441.1  1074.4   470.5 1074.98   558.8 1078.22
   578.4  1078.8   588.2 1079.54     598 1080.61   627.4 1084.35   686.2 1092.06
#Mann= 4 ,-1 , 0
       0     .12       0  101.96    .045       0  121.02     .12       0
  152.92     .06       0
Bank Sta=101.96,121.02
XS Rating Curve= 0 ,0
Exp/Cntr=0.3,0.1

Type RM Length L Ch R = 1 ,2908.8  ,289,268.9,247.4
XS GIS Cut Line= 3
     1770650.956      252468.039     1770699.567      252870.817
     1770993.317      253078.976
#Sta/Elev= 30
       0 1104.66    48.3 1084.18      58 1080.14    67.6 1076.44    77.3 1072.37
    86.9 1067.35    96.6 1062.92   115.9 1059.41  117.361059.322   125.6 1058.82
  132.241059.237   144.9 1060.33   154.6 1060.84   164.2 1060.94   212.5 1060.97
   280.1  1060.8   328.4  1061.1   367.1 1060.69   376.7 1060.99   386.4  1061.6
   405.7 1063.21  469.331066.315   483.5  1067.2     503 1068.69   541.9 1072.22
   629.5 1079.83   678.2 1083.12   746.3 1088.35     756 1089.28   765.7 1090.41
#Mann= 4 ,-1 , 0
       0     .12       0  117.36    .045       0  132.24     .12       0
  469.33     .06       0
#XS Ineff= 2 , 0
                          335.19         1065.71
Permanent Ineff=
       F       F
Bank Sta=117.36,132.24
XS Rating Curve= 0 ,0
Exp/Cntr=0.3,0.1

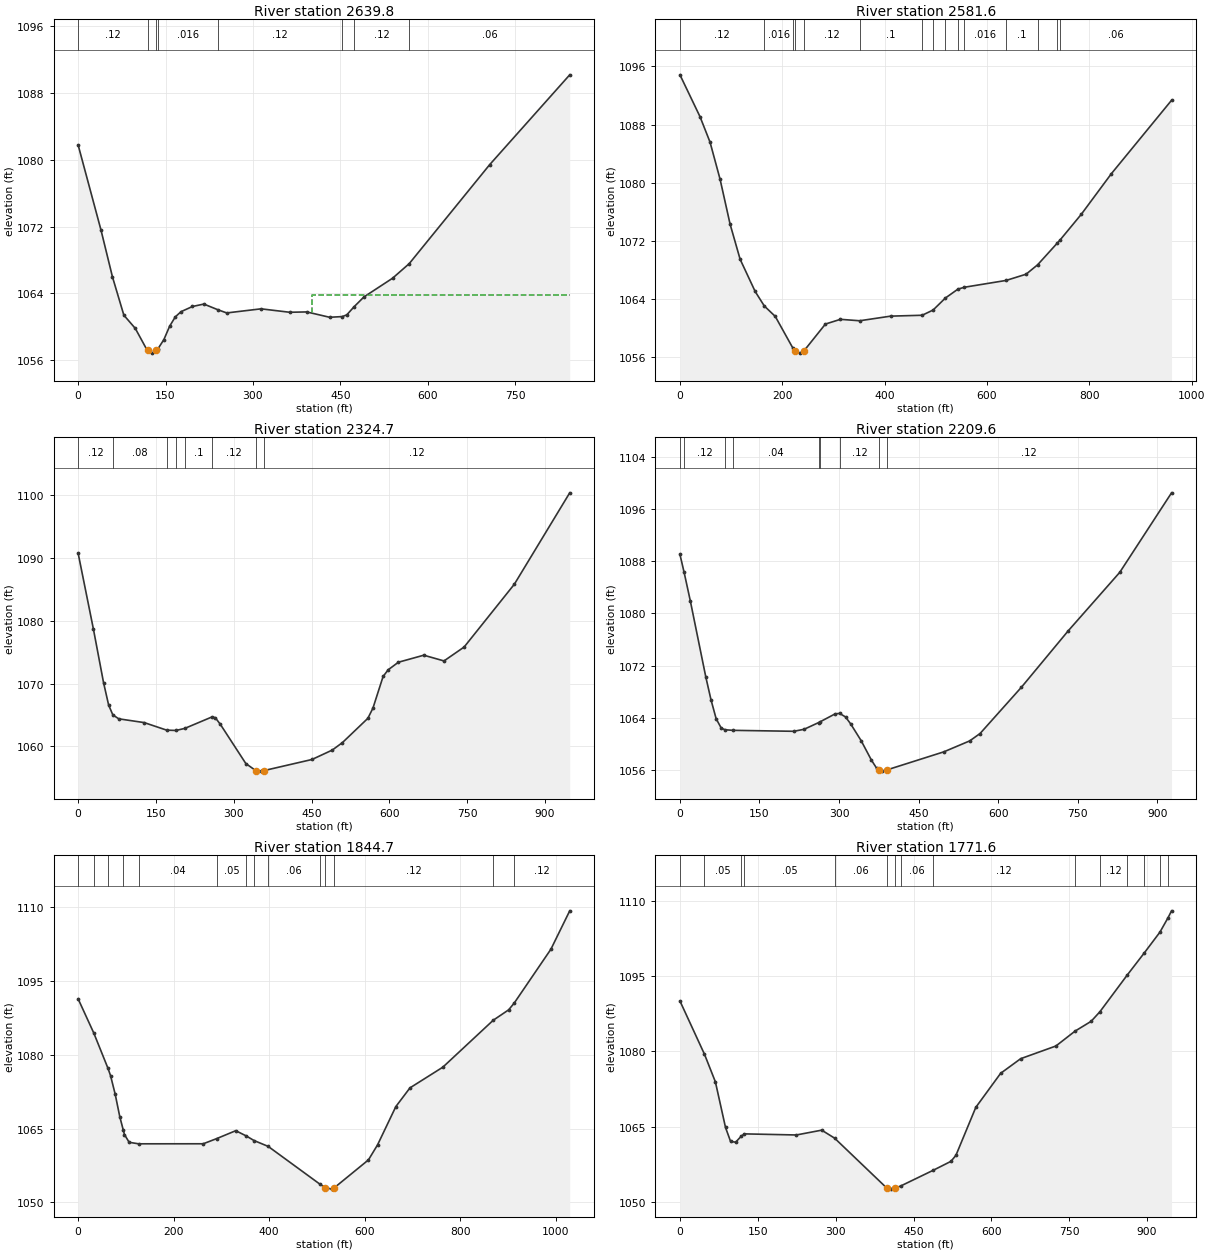
Type RM Length L Ch R = 1 ,2639.8  ,56.6,58.2,61
XS GIS Cut Line= 2
      1770305.47      252586.962     1770984.202      253088.091
#Sta/Elev= 30
       0 1081.77    39.2  1071.6    58.9 1065.99    78.5  1061.4    98.1 1059.82
   117.7 1057.31  120.021057.205   127.5 1056.86  133.631057.192  136.951057.372
   147.2 1058.48     157 1060.07   166.8  1061.2   176.6 1061.82   196.2 1062.44
   215.8 1062.73   240.71062.027   255.1 1061.67   313.9 1062.16     363 1061.75
   392.4 1061.79   431.6 1061.15  453.251061.232   461.1 1061.44  473.47  1062.4
   490.5 1063.58   539.6 1065.82  568.211067.565   706.3 1079.41   843.7 1090.16
#Mann= 8 ,-1 , 0
       0     .12       0  120.02    .045       0  133.63     .12       0
  136.95    .016       0   240.7     .12       0  453.25      .1       0
  473.47     .12       0  568.21     .06       0
#XS Ineff= 2 , 0
                          401.44         1063.78
Permanent Ineff=
       F       F
Bank Sta=120.02,133.63
XS Rating Curve= 0 ,0
Exp/Cntr=0.3,0.1

Type RM Length L Ch R = 1 ,2581.6  ,256.5,257,255.7
XS GIS Cut Line= 2
     1770180.817      252563.351     1770952.952      253134.966
#Sta/Elev= 30
       0 1094.85    39.2 1089.08    58.8 1085.57    78.4 1080.46      98 1074.26
   117.6 1069.42     147 1064.98   164.91062.976   186.3 1061.54  220.571057.188
   225.5 1056.72   235.3 1056.48  241.761056.738   284.3 1060.49   313.7 1061.14
  351.211060.942   411.7 1061.58  473.331061.701  494.711062.422  518.831064.083
  543.271065.304  556.041065.565  637.541066.505   676.4 1067.36  698.921068.655
   737.51071.658   742.11072.015   784.2 1075.61   843.1 1081.22   960.7 1091.34
#Mann= 15 ,-1 , 0
       0     .12       0   164.9    .016       0  220.57     .12       0
   225.5    .045       0  241.76     .12       0  351.21      .1       0
  473.33    .016       0  494.71     .05       0  518.83    .016       0
  543.27     .05       0  556.04    .016       0  637.54      .1       0
  698.92     .12       0   737.5      .1       0   742.1     .06       0
Bank Sta=225.5,241.76
XS Rating Curve= 0 ,0
Exp/Cntr=0.3,0.1

Type RM Length L Ch R = 1 ,2324.7  ,116.3,115.1,115.8
XS GIS Cut Line= 3
     1770038.773      252764.961     1770622.541      253125.204
      1770765.77      253344.388
#Sta/Elev= 30
       0 1090.75    29.4 1078.71      49 1070.17    58.8  1066.6   66.941065.022
    78.4  1064.4   127.4  1063.8   170.61062.603  188.591062.547  205.671062.877
  258.35 1064.71   264.6 1064.57   274.4  1063.5   323.4 1057.28     343 1056.14
   352.8 1056.08  358.05 1056.16   450.8 1057.93     490 1059.43   509.6 1060.62
   558.6 1064.48   568.4  1066.1     588 1071.14   597.8  1072.2   617.4  1073.4
   666.4 1074.52   705.4 1073.61   744.2 1075.82   841.1 1085.82   947.8 1100.35
#Mann= 8 ,-1 , 0
       0     .12       0   66.94     .08       0   170.6      .1       0
  188.59     .05       0  205.67      .1       0  258.35     .12       0
     343    .045       0  358.05     .12       0
Bank Sta=343,358.05
XS Rating Curve= 0 ,0
Exp/Cntr=0.3,0.1

Type RM Length L Ch R = 1 ,2209.6  ,342.7,364.9,386.2
XS GIS Cut Line= 2
     1769965.105      252841.563     1770742.449      253346.772
#Sta/Elev= 30
       0 1089.04    7.771086.336    19.5 1081.95    48.8 1070.24    58.6 1066.74
    68.3 1063.84    78.1 1062.38   85.511062.151   99.971062.068   214.7 1061.92
   234.2 1062.23  261.381063.251  263.591063.344   292.8  1064.6   301.21064.661
   312.3 1064.12     322 1063.05   341.6  1060.5   361.1  1057.5   370.8 1056.27
   375.8 1056.04   380.6 1055.81   390.8 1056.01   497.7 1058.77   546.5 1060.45
     566 1061.58   644.1 1068.69   731.9  1077.3   829.5 1086.31   927.1  1098.5
#Mann= 9 ,-1 , 0
       0     .06       0    7.77     .12       0   85.51     .06       0
   99.97     .04       0  261.38     .05       0  263.59      .1       0
   301.2     .12       0   375.8    .045       0   390.8     .12       0
Bank Sta=375.8,390.8
XS Rating Curve= 0 ,0
Exp/Cntr=0.3,0.1

Type RM Length L Ch R = 1 ,1844.7  ,82.5,73.2,63.5
XS GIS Cut Line= 4
     1769804.398      253014.527      1770136.43      253151.246
      1770145.11      253457.235     1770427.228       253687.27
#Sta/Elev= 30
       0 1091.39   32.941084.401   62.351077.293    67.9 1075.76    77.6 1071.99
    87.3 1067.37   94.521064.698      97 1063.78   106.8  1062.2  126.69 1061.89
     262  1061.9  290.411062.963     330 1064.56  351.86  1063.5  368.291062.556
  397.82 1061.37  506.251053.675  517.361052.971   531.3 1052.67  536.261052.941
   607.8 1058.62   626.9 1061.68   665.2 1069.47   694.7 1073.27   763.6 1077.49
  869.061087.037   901.3 1089.15  913.071090.543   989.8 1101.49  1029.2  1109.3
#Mann= 14 ,-1 , 0
       0     .12       0   32.94     .06       0   62.35      .1       0
   94.52     .06       0  126.69     .04       0  290.41     .05       0
  351.86     .06       0  368.29     .12       0  397.82     .06       0
  506.25     .12       0  517.36    .045       0  536.26     .12       0
  869.06    .016       0  913.07     .12       0
Bank Sta=517.36,536.26
XS Rating Curve= 0 ,0
Exp/Cntr=0.3,0.1

Type RM Length L Ch R = 1 ,1771.6  ,57.1,58.9,60.8
XS GIS Cut Line= 4
     1769797.969      253030.933     1770024.531      253200.203
     1770148.229      253521.818     1770398.229      253721.037
#Sta/Elev= 30
       0 1090.04   47.291079.434    68.3 1073.94    87.8 1064.86    97.5  1062.1
   107.3 1061.93  118.191063.137  124.321063.588   224.3 1063.37   273.1 1064.33
  297.92 1062.74   398.4 1052.81   407.2 1052.59   413.4 1052.72  426.181053.259
  488.171056.356   522.1 1058.12   531.7 1059.32     570 1068.87   617.8 1075.64
   656.5 1078.56   724.3 1081.08  761.29 1084.05   792.1 1085.99     809 1087.89
  861.121095.126  894.881099.654  924.621103.734  940.171106.583   947.1 1107.99
#Mann= 15 ,-1 , 0
       0     .12       0   47.29     .05       0  118.19      .1       0
  124.32     .05       0  297.92     .06       0   398.4    .045       0
   413.4     .12       0  426.18     .06       0  488.17     .12       0
  761.29    .016       0     809     .12       0  861.12     .06       0
  894.88     .12       0  924.62     .06       0  940.17     .12       0
Bank Sta=398.4,413.4
XS Rating Curve= 0 ,0
Exp/Cntr=0.3,0.1

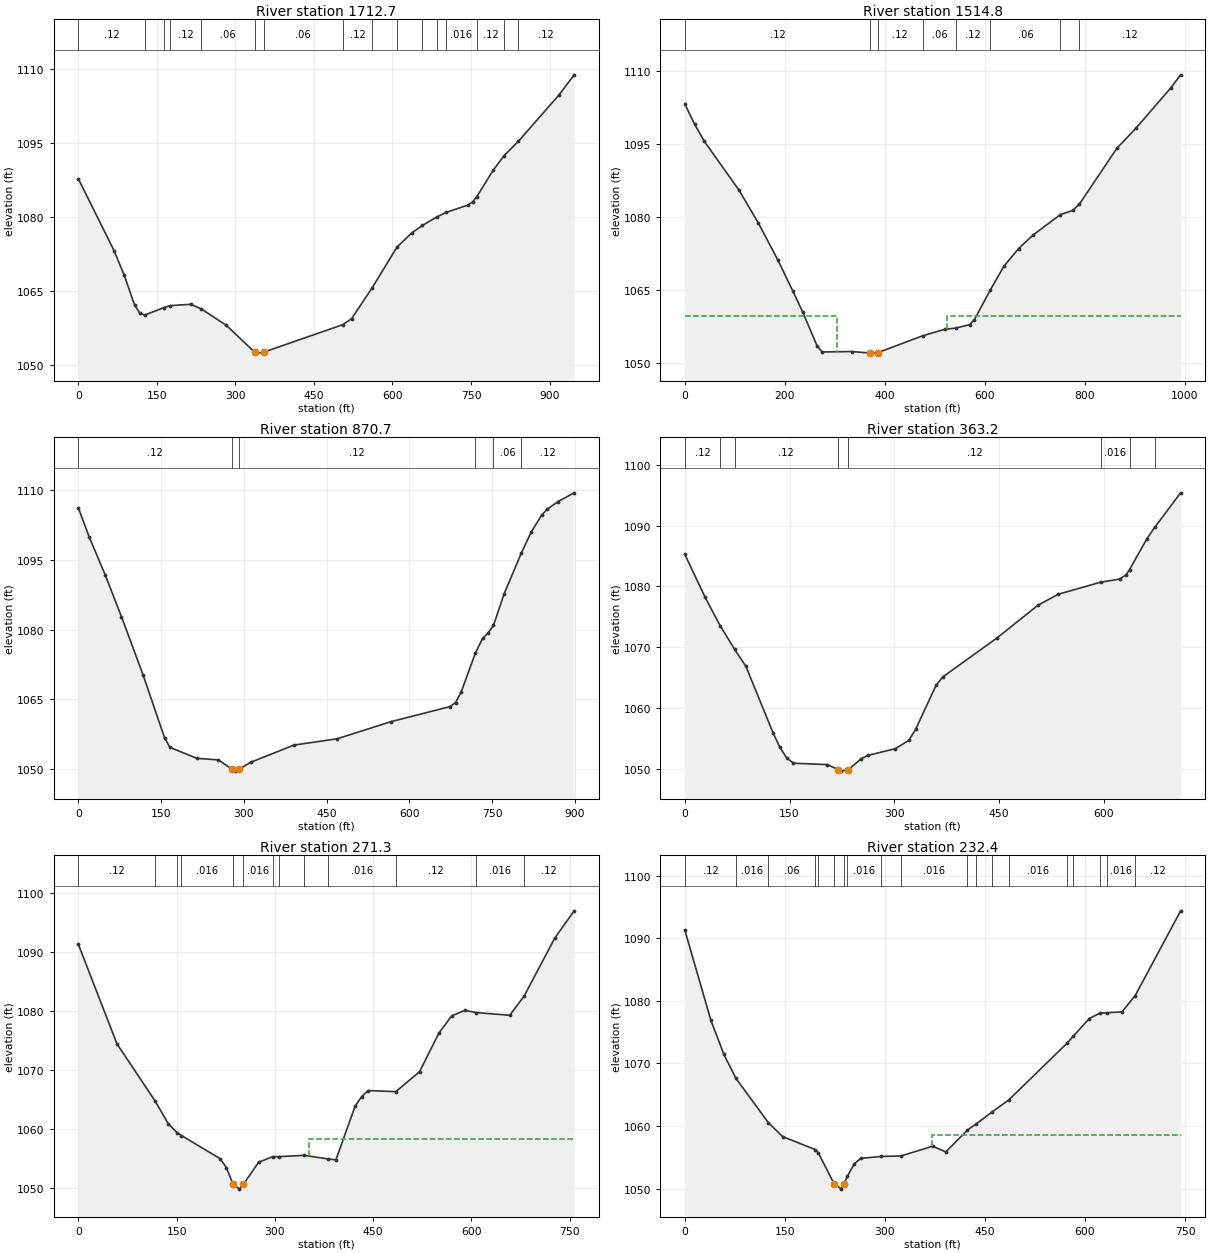
Type RM Length L Ch R = 1 ,1712.7  ,211.7,198,184.5
XS GIS Cut Line= 4
     1769762.812      253093.433     1769989.375      253262.703
     1770113.073      253584.318     1770363.073      253783.537
#Sta/Elev= 30
       0 1087.77    68.3 1073.21    87.8  1068.2   107.3 1062.25     117 1060.62
   126.61060.169  163.941061.692  175.351062.075   214.6 1062.35  234.911061.418
   282.8 1058.08  337.15 1052.62   340.2 1052.46  353.92 1052.65  505.151058.224
   522.1 1059.45  561.52 1065.74  608.591073.923   637.1 1076.82  657.341078.316
   685.11080.066  702.551080.956   743.6 1082.42   753.3  1083.1   761.11084.153
   792.1 1089.45   813.5 1092.48  840.571095.358     918 1104.73   947.1 1108.82
#Mann= 16 ,-1 , 0
       0     .12       0   126.6     .06       0  163.94     .05       0
  175.35     .12       0  234.91     .06       0  337.15    .045       0
  353.92     .06       0  505.15     .12       0  561.52     .06       0
  608.59     .12       0  657.34     .06       0   685.1     .12       0
  702.55    .016       0   761.1     .12       0   813.5     .06       0
  840.57     .12       0
Bank Sta=337.15,353.92
XS Rating Curve= 0 ,0
Exp/Cntr=0.3,0.1

Type RM Length L Ch R = 1 ,1514.8  ,633.7,644.1,644.8
XS GIS Cut Line= 2
     1769557.003      253203.329     1770344.763      253806.628
#Sta/Elev= 30
       0 1103.25    19.6  1099.1    39.3 1095.53   108.1 1085.57   147.4 1078.72
   186.7 1071.04   216.1 1064.77   235.8 1060.46   265.2 1053.35   275.1 1052.21
     334  1052.3   370.7 1051.99   373.3 1051.97   385.7 1052.05  476.671055.566
   520.7 1056.89  542.561057.126   569.8 1057.82   579.6 1058.88  611.431064.974
   638.6 1069.87     668  1073.5   697.5 1076.33  751.761080.486   776.1 1081.34
  789.551082.627   864.5 1094.11   903.8 1098.38   972.6 1106.57   992.2 1109.25
#Mann= 8 ,-1 , 0
       0     .12       0   370.7    .045       0   385.7     .12       0
  476.67     .06       0  542.56     .12       0  611.43     .06       0
  751.76    .016       0  789.55     .12       0
#XS Ineff= 2 , 0
          304.44 1059.63  524.25         1059.63
Permanent Ineff=
       F       F
Bank Sta=370.7,385.7
XS Rating Curve= 0 ,0
Exp/Cntr=0.3,0.1

Type RM Length L Ch R = 1 ,870.7   ,502.6,507.5,503.8
XS GIS Cut Line= 2
     1769321.095      253483.447     1769837.067      254219.601
#Sta/Elev= 30
       0 1106.26    19.5 1100.04    48.9 1091.76    78.2 1082.81   117.3  1070.3
   156.3 1056.74   166.1 1054.66     215 1052.29   254.1 1051.96  278.16 1049.97
   283.4 1049.54   291.7 1049.96   312.7 1051.46   390.9 1055.15     469  1056.5
   566.7 1060.19   674.2 1063.45     684 1064.31   693.8  1066.5  719.931074.973
   732.9 1078.12   742.6 1079.25  752.751080.939   771.9  1087.7  803.211096.508
   820.8 1100.98   840.3 1104.74   850.1 1105.95   869.7  1107.6     899 1109.49
#Mann= 6 ,-1 , 0
       0     .12       0  278.16    .045       0   291.7     .12       0
  719.93    .016       0  752.75     .06       0  803.21     .12       0
Bank Sta=278.16,291.7
XS Rating Curve= 0 ,0
Exp/Cntr=0.3,0.1

Type RM Length L Ch R = 1 ,363.2   ,101.1,91.9,89.2
XS GIS Cut Line= 2
     1769083.912       253843.52     1769494.069      254422.947
#Sta/Elev= 30
       0 1085.28    29.2 1078.21   50.461073.594   71.451069.662    87.5  1066.9
   126.4 1055.98   136.2  1053.6   145.9 1051.88   155.6 1051.01   204.2 1050.78
   219.3 1049.97   223.7 1049.71   234.3 1049.96   252.8 1051.76   262.6 1052.31
   301.5 1053.39   320.9 1054.77   330.6  1056.6   359.8  1063.8   369.5 1065.17
   447.3 1071.58   505.7 1076.93   534.9 1078.73  595.471080.703   622.4 1081.21
   632.1 1081.95  636.711082.758   661.3 1087.76  673.331089.785   709.9 1095.36
#Mann= 8 ,-1 , 0
       0     .12       0   50.46     .06       0   71.45     .12       0
   219.3    .045       0   234.3     .12       0  595.47    .016       0
  636.71     .06       0  673.33     .12       0
Bank Sta=219.3,234.3
XS Rating Curve= 0 ,0
Exp/Cntr=0.3,0.1

Type RM Length L Ch R = 1 ,271.3   ,38,38.9,38.8
XS GIS Cut Line= 2
     1768986.893      253881.667     1769456.858       254474.81
#Sta/Elev= 30
       0  1091.3      59  1074.4  117.03 1064.73   137.6 1060.79  150.62 1059.35
  157.451058.841   216.2 1054.94     226  1053.4   235.9 1050.66   245.7 1049.75
  252.071050.589   275.2 1054.32  296.381055.245  306.251055.264  344.971055.483
  380.651054.882   393.1 1054.71   422.6 1063.87   432.4 1065.44   442.3 1066.48
  484.651066.295   520.9 1069.69   550.4 1076.25     570 1079.16   589.7 1080.08
  607.281079.716   658.5 1079.25  680.611082.547   727.3 1092.37   756.8 1096.98
#Mann= 13 ,-1 , 0
       0     .12       0  117.03    .016       0  150.62     .06       0
  157.45    .016       0   235.9    .045       0  252.07    .016       0
  296.38     .06       0  306.25    .016       0  344.97     .06       0
  380.65    .016       0  484.65     .12       0  607.28    .016       0
  680.61     .12       0
#XS Ineff= 2 , 0
                          352.53         1058.24
Permanent Ineff=
       F       F
Bank Sta=235.9,252.07
XS Rating Curve= 0 ,0
Exp/Cntr=0.3,0.1

Type RM Length L Ch R = 1 ,232.4   ,159.2,152.9,146.6
XS GIS Cut Line= 2
     1768959.766      253907.709     1769423.004      254489.133
#Sta/Elev= 30
       0 1091.32    39.1 1076.89    58.7 1071.44    76.81067.606  125.481060.523
   146.7 1058.33  195.261056.266  200.031055.766  223.71 1050.82   234.8 1049.94
  238.62  1050.8  243.681051.973   254.3 1054.02   264.1 1054.85   294.3 1055.16
  323.991055.227   371.7  1056.8   391.3 1055.88   423.71059.368  437.351060.385
  460.971062.279  485.761064.181   572.81073.203   582.61074.369   606.5 1077.18
  621.891078.013  632.391078.104   655.4 1078.23  675.291080.842   743.4 1094.37
#Mann= 19 ,-1 , 0
       0     .12       0    76.8    .016       0  125.48     .06       0
  195.26    .016       0  200.03     .12       0  223.71    .045       0
  238.62     .12       0  243.68    .016       0   294.3     .06       0
  323.99    .016       0   423.7     .12       0  437.35    .016       0
  460.97     .12       0  485.76    .016       0   572.8     .12       0
   582.6    .016       0  621.89     .08       0  632.39    .016       0
  675.29     .12       0
#XS Ineff= 2 , 0
                          370.69         1058.55
Permanent Ineff=
       F       F
Bank Sta=223.71,238.62
XS Rating Curve= 0 ,0
Exp/Cntr=0.3,0.1

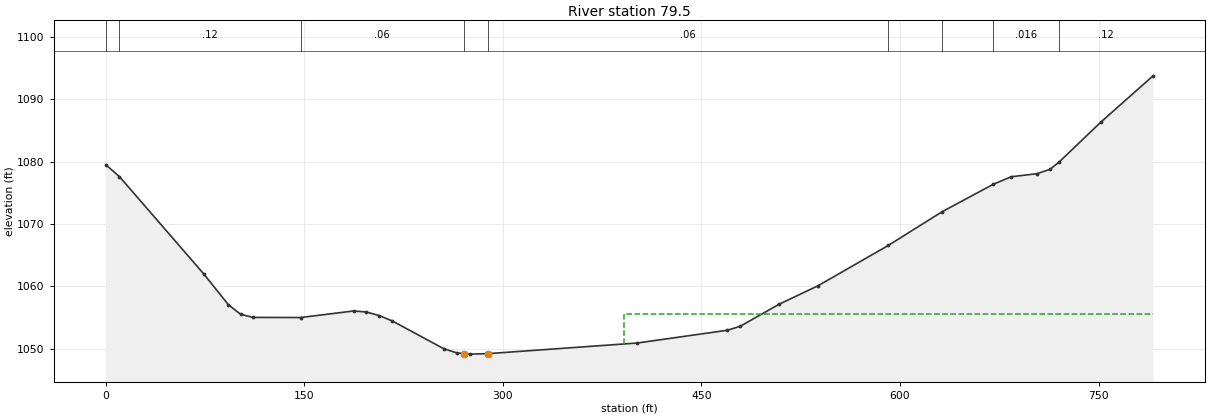
Type RM Length L Ch R = 1 ,79.5    ,99.4,79.5,58.6
XS GIS Cut Line= 3
     1768878.723      253971.308     1768893.575      254118.645
     1769416.494      254493.039
#Sta/Elev= 30
       0 1079.47   10.241077.583      74 1061.96    92.6 1057.02   101.8  1055.5
   111.1    1055  147.111054.981   187.1 1056.03   196.8 1055.87   206.6 1055.29
   216.3 1054.44   255.3 1049.98     265 1049.32  270.43 1049.19   274.8 1049.11
  288.85 1049.19   401.4 1050.89   469.6 1052.94   479.4 1053.59   508.6 1057.11
   537.9 1060.06  591.211066.548   631.51071.913  670.591076.366     684 1077.56
   703.5 1078.05   713.3 1078.75     7201079.883   752.2 1086.41   791.2 1093.75
#Mann= 9 ,-1 , 0
       0    .016       0   10.24     .12       0  147.11     .06       0
  270.43    .045       0  288.85     .06       0  591.21     .08       0
   631.5     .06       0  670.59    .016       0     720     .12       0
#XS Ineff= 2 , 0
                          391.33         1055.61
Permanent Ineff=
       F       F
Bank Sta=270.43,288.85
XS Rating Curve= 0 ,0
Exp/Cntr=0.3,0.1

Chan Stop Cuts=-1
Use User Specified Reach Order=0
Composite Channel Slope=5